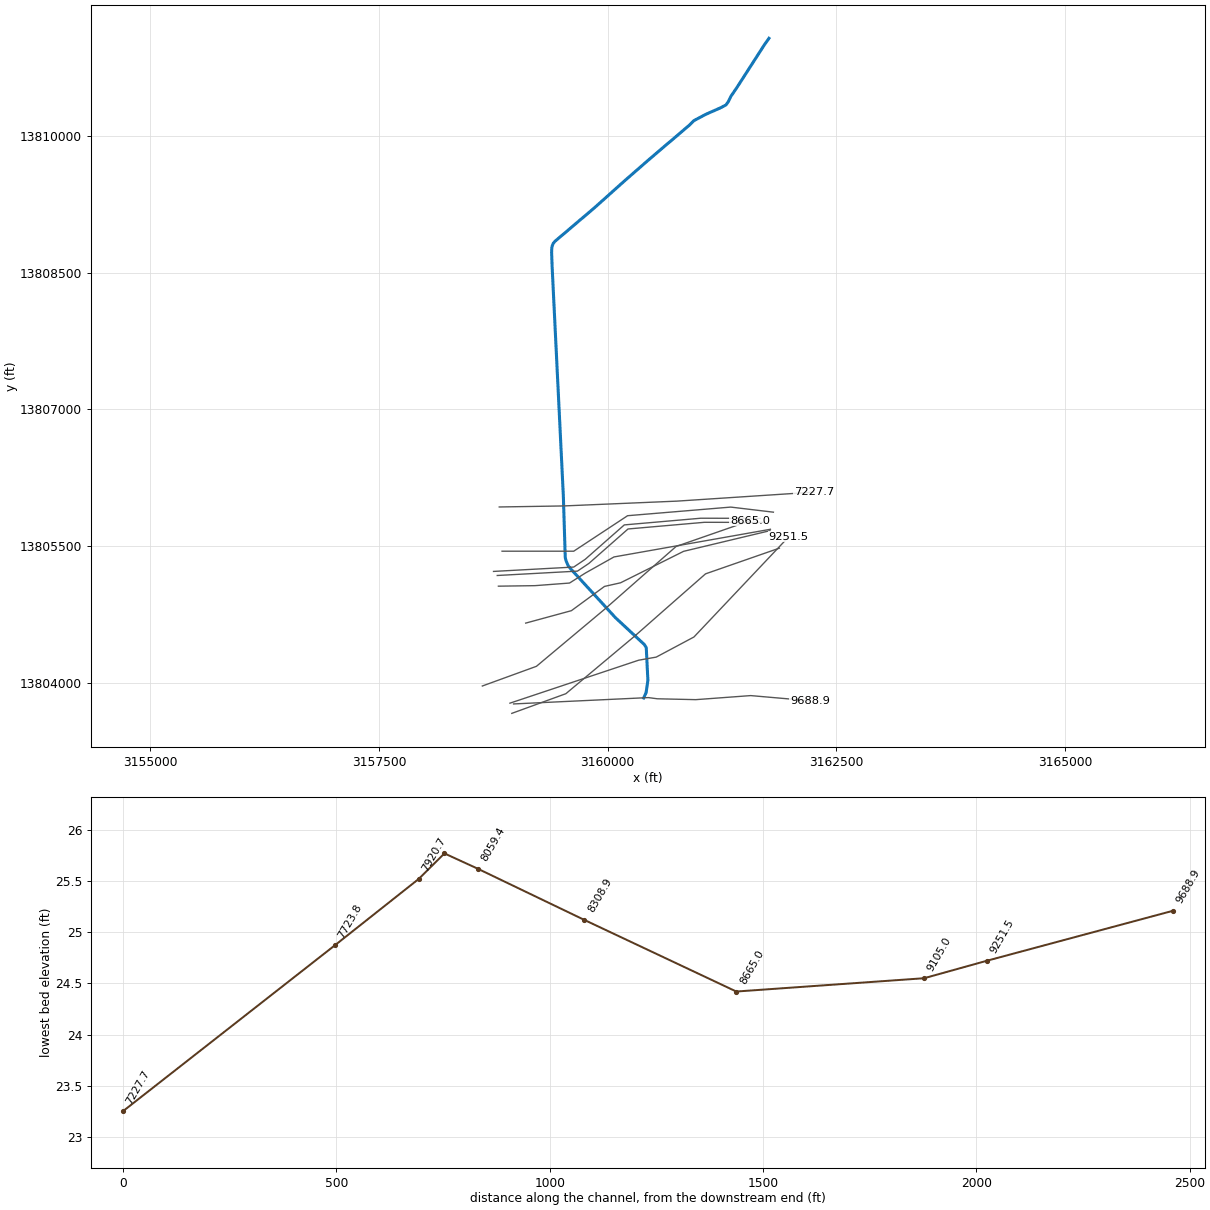
--- C106-03-00.PRJ (project) ---

Proj Title=C106-03-00
Current Plan=p02
Default Exp/Contr=0.3,0.1
English Units
Geom File=g01
Flow File=f01
Flow File=f02
Plan File=p01
Plan File=p02
Y Axis Title=Elevation
X Axis Title(PF)=Main Channel Distance
X Axis Title(XS)=Station
BEGIN DESCRIPTION:
Sims Bayou Watershed
Berry Bayou Tributary 2.0
HCFCD Unit C106-03-00
Flood Hazard Model
10, 2, 1, 0.2% Event
Filename C106-03-00.prj
Prepared by:  Watershed Concepts  Date:
Reviewed by:                      Date:
STATUS FINAL
END DESCRIPTION:
DSS Export Rating Curves= 0
DSS Export Rating Curve Sorted= 0
DSS Export Volume Flow Curves= 0
DXF OffsetX= 0
DXF OffsetY= 0
DXF ScaleX= 1
DXF ScaleY= 10

--- C106-03-00.p02 (plan) ---

Plan Title=Effective Floodway 2015
Program Version=4.10
Short Identifier=Eff+RiskMAP FW
Geom File=g01
Flow File=f02
Subcritical Flow
K Sum by GR= 0
Std Step Tol= 0.01
Critical Tol= 0.01
Num of Std Step Trials= 20
Max Error Tol= 0.3
Flow Tol Ratio= 0.001
Split Flow NTrial= 30
Split Flow Tol= 0.02
Split Flow Ratio= 0.02
Log Output Level= 0
Friction Slope Method= 1
Unsteady Friction Slope Method= 2
Unsteady Bridges Friction Slope Method= 1
Parabolic Critical Depth
Global Vel Dist= 0 , 0 , 0
Global Log Level= 0
CheckData=True
Encroach Param=-1 ,0,0, 2
Encroach River=C106-03-00
Encroach Reach=C106-03-00_0010
Encroach Node=9688.9
       1    4650    5540
Encroach Node=9251.5
       1    4625    5700
Encroach Node=9105.0
       1    4740    6000
Encroach Node=8665.0
       1    4960    6150
Encroach Node=8308.9
       1    4960    6150
Encroach Node=8059.4
       1    4960    6240
Encroach Node=7981.1
       1    4935    6260
Encroach Node=7920.7
       1    4925    6300
Encroach Node=7723.8
       1    4850    6260
Encroach Node=7227.7
       1    4800    6120
Encroach Node=6249.2
       1    4900    5800
Encroach Node=6090.6
       1    4760    5650
Encroach Node=6050.0
       1    4760    5650
Encroach Node=5759.9
       1    4955    5500
Encroach Node=5275.3
       1    4960  5025.3
Encroach Node=4551.7
       1  4965.7  5025.3
Encroach Node=4360.0
       1    4950  5025.3
Encroach Node=3715.2
       1    4971    5030
Encroach Node=3593.4
       1    4968    5030
Encroach Node=3542.4
       1    4968    5030
Encroach Node=3317.0
       1  4975.9    5033
Encroach Node=2769.2
       1  4975.9  5027.1
Encroach Node=2643.6
       1  4975.9  5027.1
Encroach Node=2590.2
       1  4975.9  5027.1
Encroach Node=2354.4
       1  4971.1  5032.9
Encroach Node=2283.4
       1  4971.1  5032.9
Encroach Node=2192.3
       1  4971.1  5032.9
Encroach Node=2134.7
       1  4971.1  5032.9
Encroach Node=1916.4
       1 4952.66  5014.6
Encroach Node=1818.4
       1 4952.66  5014.6
Encroach Node=1723.5
       1  4967.4  5030.3
Encroach Node=1699.5
       1  4967.4  5030.3
Encroach Node=1672.2
       1  4970.6 5028.34
Encroach Node=1661.0
       1  4970.6  5028.3
Encroach Node=1575.0
       1 4970.17 5030.87
Encroach Node=1563.5
       1 4970.17 5030.87
Encroach Node=1497.0
       1  4968.8  5037.8
Encroach Node=1456.4
       1  4968.8  5037.8
Encroach Node=1348.9
       1  4967.4  5039.7
Encroach Node=1217.3
       1  4967.4  5039.7
Encroach Node=1137.3
       1  4967.4  5039.7
Encroach Node=1049.0
       1  4968.6  5031.7
BEGIN DESCRIPTION:
FEMA Effective Risk Map Study Floodway May 02, 2019
END DESCRIPTION:
Computation Interval=1HOUR
Output Interval=1HOUR
Run HTab= 0
Run UNet= 0
Run PostProcess= 0
Run WQNet= 0
UNET Theta= 1
UNET Theta Warmup= 1
UNET ZTol= 0.02
UNET ZSATol= 0.1
UNET MxIter= 20
UNET MaxInSteps= 20
UNET DtIC= 0
UNET DtMin= 0
UNET MaxCRTS= 20
UNET WFStab= 2
UNET SFStab= 1
UNET WFX= 1
UNET SFX= 1
UNET DSS MLevel= 4
UNET DZMax Abort= 100
UNET Convert EG Bridges=-1
UNET Use Existing IB Tables=-1
UNET Froude Reduction=False
UNET Froude Limit= 1
UNET Froude Power= 10
UNET Time Slicing=0,0, 5
UNET Junction Losses=0
Instantaneous Interval=1HOUR
Write IC File= 0
IC Time=0,,
Write IC File at Sim End=0
Echo Input=False
Echo Parameters=False
Echo Output=False
Write Detailed= 0
WQ AD Non Conservative
WQ ULTIMATE=-1
WQ Max Comp Step=1HOUR
WQ Output Interval=15MIN
WQ Output Selected Increments= 0
WQ Output face flow=0
WQ Output face velocity=0
WQ Output face area=0
WQ Output face dispersion=0
WQ Output cell volume=0
WQ Output cell surface area=0
WQ Output cell continuity=0
WQ Output cumulative cell continuity=0
WQ Output face conc=0
WQ Output face dconc_dx=0
WQ Output face courant=0
WQ Output face peclet=0
WQ Output face adv mass=0
WQ Output face disp mass=0
WQ Output cell mass=0
WQ Output cell source sink temp=0
WQ Output cell source sink nsm=0
WQ Output MaxMinRange=-1
WQ Daily Max Min Mean=-1
WQ Daily Range=0
WQ Daily Time=0
WQ Create Restart=0
WQ Fixed Restart=0
WQ System Summary=0
WQ Use Fixed Temperature=0
Sorting and Armoring Iterations= 10
XS Update Threshold= 0.02
Hydraulics Update Threshold= 0.02
Energy Slope Method= 1
Volume Change Method= 0
XS Weighting Method= 0
Number of US Weighted Cross Sections= 1
Number of DS Weighted Cross Sections= 1
Upstream XS Weight=0.25
Main XS Weight=0.5
Downstream XS Weight=0.25
Number of DS XS's Weighted with US Boundary= 1
Upstream Boundary Weight= 1
Weight of XSs Associated with US Boundary= 0
Number of US XS's Weighted with DS Boundary= 1
Downstream Boundary Weight= 0.5
Weight of XSs Associated with DS Boundary= 0.5
Sediment Output Level= 4
Mass or Volume Output= 0
Output Increment Type= 1
Profile and TS Output Increment= 10
XS Output Flag= 0
XS Output Increment= 10
Disregard all LS=0
Disregard all Conn=0
Disregard all Breaches=0
Disregard all Pumps=0

--- C106-03-00.p01 (plan) ---

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Plan Title=Effective Multi-Profile 2015
Short Identifier=Eff+RiskMAP MP
Geom File=g01
Flow File=f02
Encroach Param=-1 ,0,0, 0
FEMA Effective Risk Map Study Multi-Profile May 02, 2019
UNET ZSATol= 0.05
UNET MaxInSteps= 0

--- C106-03-00.f02 (steady flow) ---

Flow Title=Effective Floodway 2015
Program Version=4.10
Number of Profiles= 2
Profile Names=1PCT_100yr,Floodway
River Rch & RM=C106-03-00,C106-03-00_0010 ,9688.9
    1325    1325
River Rch & RM=C106-03-00,C106-03-00_0010 ,7950.9
    1424    1424
River Rch & RM=C106-03-00,C106-03-00_0010 ,6070.3
    1623    1623
River Rch & RM=C106-03-00,C106-03-00_0010 ,3567.9
    1920    1920
River Rch & RM=C106-03-00,C106-03-00_0010 ,2616.9
    2033    2033
River Rch & RM=C106-03-00,C106-03-00_0010 ,2163.5
    2157    2157
River Rch & RM=C106-03-00,C106-03-00_0010 ,1661.7
    2248    2248
Boundary for River Rch & Prof#=C106-03-00,C106-03-00_0010 , 1
Up Type= 0
Dn Type= 3
Dn Slope=0.0064
Boundary for River Rch & Prof#=C106-03-00,C106-03-00_0010 , 2
Up Type= 0
Dn Type= 1
Dn Known WS=20.97
DSS Import GetInterval= 0
DSS Import GetPeak= 0
DSS Import FillOption= 0

--- C106-03-00.f01 (steady flow) ---

Flow Title=Effective Multi-Profile 2015
Program Version=4.10
Number of Profiles= 6
Profile Names=10PCT_10yr,4PCT_25yr,2PCT_50yr,1PCT_100yr,1PCT_Plus,0.2PCT_500yr
River Rch & RM=C106-03-00,C106-03-00_0010 ,9688.9
     765     956    1132    1325    1590    1888
River Rch & RM=C106-03-00,C106-03-00_0010 ,7950.9
     822    1027    1216    1424    1708    2028
River Rch & RM=C106-03-00,C106-03-00_0010 ,6070.3
     938    1172    1388    1623    1948    2313
River Rch & RM=C106-03-00,C106-03-00_0010 ,3567.9
    1109    1387    1641    1920    2304    2735
River Rch & RM=C106-03-00,C106-03-00_0010 ,2616.9
    1175    1469    1738    2033    2440    2897
River Rch & RM=C106-03-00,C106-03-00_0010 ,2163.5
    1247    1558    1844    2157    2588    3074
River Rch & RM=C106-03-00,C106-03-00_0010 ,1661.7
    1299    1624    1922    2248    2697    3203
Boundary for River Rch & Prof#=C106-03-00,C106-03-00_0010 , 1
Up Type= 0
Dn Type= 3
Dn Slope=0.0064
Boundary for River Rch & Prof#=C106-03-00,C106-03-00_0010 , 2
Up Type= 0
Dn Type= 3
Dn Slope=0.0064
Boundary for River Rch & Prof#=C106-03-00,C106-03-00_0010 , 3
Up Type= 0
Dn Type= 3
Dn Slope=0.0064
Boundary for River Rch & Prof#=C106-03-00,C106-03-00_0010 , 4
Up Type= 0
Dn Type= 3
Dn Slope=0.0064
DSS Import GetInterval= 0
DSS Import GetPeak= 0
DSS Import FillOption= 0

--- C106-03-00.g01 (geometry) ---

Geom Title=C106-03-00 2015
Program Version=4.10

River Reach=C106-03-00      ,C106-03-00_0010
Reach XY= 30
      3160395.19      13803838.2      3160421.75       13803897.
      3160441.25       13804032.       3160423.5       13804389.
      3160403.25       13804423.       3160084.5       13804720.
       3159608.5       13805241.        3159572.       13805283.
      3159549.25       13805334.      3159537.75       13805376.
        3159517.       13806048.      3159394.25       13808562.
       3159388.5       13808720.      3159390.25       13808770.
        3159397.       13808798.       3159407.5       13808821.
       3159426.5       13808843.      3159855.75       13809208.
      3160191.25       13809509.       3160468.5       13809751.
      3160895.25       13810115.        3160944.       13810164.
       3161073.5       13810233.      3161234.25       13810304.
       3161294.5       13810336.      3161321.25       13810373.
        3161348.       13810429.       3161412.5       13810524.
      3161713.75       13810993.      3161764.75       13811066.

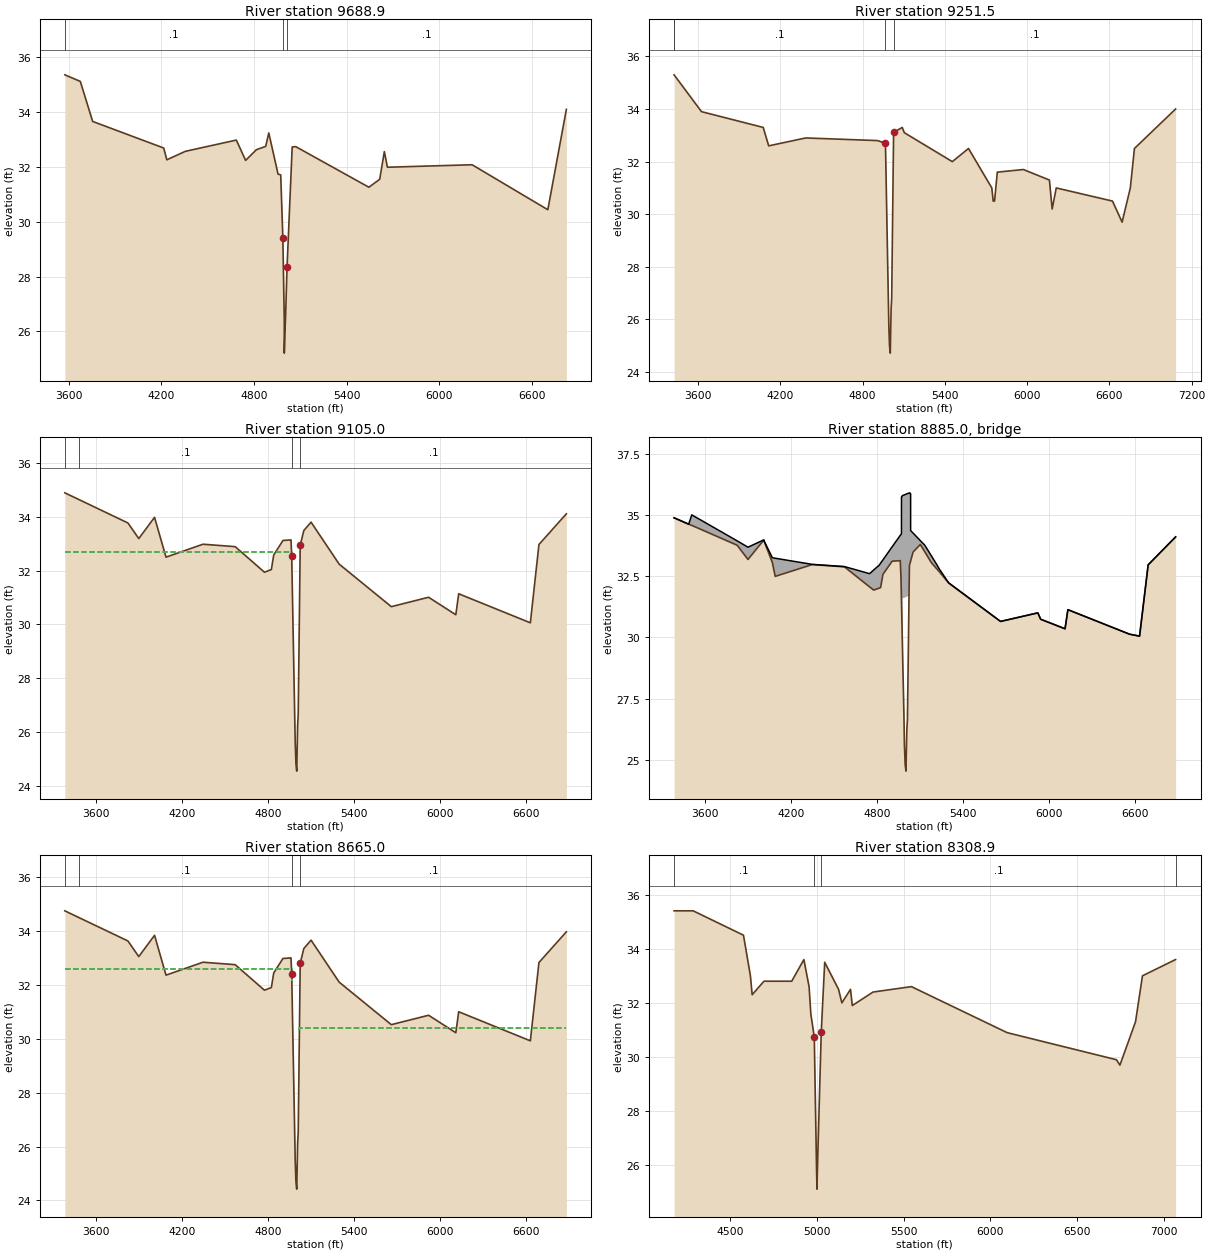
Type RM Length L Ch R = 1 ,9688.9  ,344.6,437.4,743.1
BEGIN DESCRIPTION:
Cross Section 9688.9
END DESCRIPTION:
XS GIS Cut Line= 6
      3158972.61     13803772.96      3160446.64     13803842.47
      3160544.74      13803829.5      3160964.48     13803819.96
      3161565.47     13803864.47      3162212.17     13803807.94
#Sta/Elev= 29
  3575.8   35.36  3675.8   35.12  3755.8   33.66  4215.8   32.69  4235.8   32.26
  4355.8   32.57  4685.8   32.98  4745.8   32.24  4815.8   32.63  4875.8   32.75
  4895.8   33.24  4945.8   31.99  4955.7   31.74  4973.1   31.71  4986.9   29.41
  4995.9   26.47  4996.2   25.21    5000   25.91  5004.2    26.5    5014   28.35
  5047.3   32.73  5070.8   32.74  5543.8   31.26  5613.8   31.55  5643.8   32.56
  5663.8   31.99  6212.1   32.08  6702.1   30.44  6822.1    34.1
#Mann= 3 , 1 , 0
  3575.8      .1       0  4986.9     .04       0    5014      .1       0
Bank Sta=4986.9,5014
XS Rating Curve= 0 ,0
Exp/Cntr=0.3,0.1

Type RM Length L Ch R = 1 ,9251.5  ,68,146.5,217.9
BEGIN DESCRIPTION:
Cross Section 9251.5-Interpolated
END DESCRIPTION:
XS GIS Cut Line= 5
      3158932.97     13803781.58      3160340.05     13804252.18
      3160532.28     13804286.11      3160945.03     13804506.61
      3161981.56     13805604.78
#Sta/Elev= 30
  3425.5    35.3  3625.5    33.9  4075.5    33.3  4115.5    32.6  4385.5    32.9
  4909.2    32.8  4966.9    32.7  4991.4   25.77  4996.5   24.99    5002   24.72
  5008.1   26.41  5012.3   26.82  5026.2   33.11  5089.2    33.3  5104.4    33.1
  5454.4      32  5572.4    32.5  5742.4      31  5752.4    30.5  5762.4    30.5
  5782.4    31.6  5972.4    31.7  6162.4    31.3  6182.4    30.2  6212.4      31
  6622.4    30.5  6692.4    29.7  6752.4      31  6782.4    32.5  7082.4      34
#Mann= 4 , 1 , 0
  3425.5      .2       0  3425.5      .1       0  4966.9     .04       0
  5026.2      .1       0
Bank Sta=4966.9,5026.2
XS Rating Curve= 0 ,0
Exp/Cntr=0.5,0.3

Type RM Length L Ch R = 1 ,9105.0  ,440,440,440
BEGIN DESCRIPTION:
Upstream Section of Bridge/Culvert/Weir
END DESCRIPTION:
XS GIS Cut Line= 6
      3158953.05      13803669.6      3159544.38     13803885.22
      3160301.18     13804519.85      3160621.61     13804802.67
      3161071.53     13805198.41      3161879.15     13805480.06
#Sta/Elev= 30
  3384.2   34.89    3486   34.63  3824.2   33.77  3899.9   33.19  4009.9   33.98
  4089.9    32.5  4347.7   32.98  4572.6   32.89  4776.8   31.94    4825   32.04
  4841.3   32.58  4905.9   33.12    4962   33.14  4966.9   32.53  4991.4    25.6
  4996.5   24.82    5002   24.55  5008.1   26.24  5012.3   26.65  5026.2   32.94
  5051.5   33.49    5102    33.8  5298.1   32.24  5661.9   30.66  5921.9   31.01
  6111.9   30.36  6131.9   31.14  6631.9   30.06  6691.9   32.97  6883.2   34.11
#Mann= 4 , 1 , 0
  3384.2      .2       0    3486      .1       0  4966.9     .04       0
  5026.2      .1       0
#XS Ineff= 2 , 0
       0    4967    32.7  5020.7       0    30.4
Permanent Ineff=
       F       F
Bank Sta=4966.9,5026.2
XS Rating Curve= 0 ,0
Exp/Cntr=0.5,0.3

Type RM Length L Ch R = 3 ,8885.0  ,,,
BEGIN DESCRIPTION:
COLLEGE AVENUE
Structure ID: C63-11
END DESCRIPTION:
Bridge Culvert--1,0,-1,-1, 0
Deck Dist Width WeirC Skew NumUp NumDn MinLoCord MaxHiCord MaxSubmerge Is_Ogee
10,420,2.6,0, 60, 60, , , 0.95, 0, 1,1,,
  3384.2    3486  3507.7  3824.2  3899.9  4009.9  4013.6  4069.9  4089.9  4347.7
  4572.6  4748.3  4776.8  4815.9    4825  4841.3  4889.1  4905.9    4962  4966.9
 4970.69  4970.8 4970.91  4977.9    4978 4978.11  4978.2  4987.7  4987.8  4991.4
  4996.5    5002  5008.1  5012.2  5012.3 5019.39  5019.5  5026.2  5027.8  5027.9
 5034.39  5034.5 5034.61  5051.5    5102  5133.7    5178  5214.9  5234.9  5298.1
  5303.9  5661.9  5921.9  5941.9  6111.9  6131.9  6561.9  6631.9  6691.9  6883.2
   34.88   34.62      35   33.94   33.68   33.98   33.92   33.25   33.23   32.98
   32.89    32.6   32.75   32.95   33.03   33.16   33.56    33.7   34.16    34.2
   34.23   35.73   35.73   35.79   35.79   35.79   35.79   35.81   35.81   35.82
   35.83   35.84   35.86   35.87   35.87   35.88   35.88    35.9    35.9    35.9
   35.86   35.86   34.36   34.26   33.95   33.76   33.34   32.99   32.79   32.24
   32.21   30.65      31   30.74   30.35   31.13   30.13   30.05   32.96    34.1
   34.88   34.62   34.57   33.76   33.18   33.97   33.91   33.05   32.49   32.97
   32.88   32.06   31.93   32.01   32.03   32.57   32.97   33.11   33.13   32.52
   31.49   31.46   31.43   29.54   29.51   29.48   31.59   31.61   31.61   31.62
   31.63   31.64   31.66   31.67   31.67   31.68    29.9   32.93   32.96   32.97
   33.11   33.11   33.11   33.48   33.79   33.49   33.06   32.81   32.68   32.23
    32.2   30.65      31   30.74   30.35   31.13   30.13   30.05   32.96    34.1
  3384.2    3486  3507.7  3824.2  3899.9  4009.9  4013.6  4069.9  4089.9  4347.7
  4572.6  4748.3  4776.8  4815.9    4825  4841.3  4889.1  4905.9    4962  4966.9
 4970.69  4970.8 4970.91  4977.9    4978 4978.11  4978.2  4987.7  4987.8  4991.4
  4996.5    5002  5008.1  5012.2  5012.3 5019.39  5019.5  5026.2  5027.8  5027.9
 5034.39  5034.5 5034.61  5051.5    5102  5133.7    5178  5214.9  5234.9  5298.1
  5303.9  5661.9  5921.9  5941.9  6111.9  6131.9  6561.9  6631.9  6691.9  6883.2
   34.88   34.62      35   33.94   33.68   33.98   33.92   33.25   33.23   32.98
   32.89    32.6   32.75   32.95   33.03   33.16   33.56    33.7   34.16    34.2
   34.23   35.73   35.73   35.79   35.79   35.79   35.79   35.81   35.81   35.82
   35.83   35.84   35.86   35.87   35.87   35.88   35.88    35.9    35.9    35.9
   35.86   35.86   34.36   34.26   33.95   33.76   33.34   32.99   32.79   32.24
   32.21   30.65      31   30.74   30.35   31.13   30.13   30.05   32.96    34.1
   34.74   34.48   34.43   33.62   33.04   33.83   33.77   32.91   32.35   32.83
   32.74   31.92   31.79   31.87   31.89   32.43   32.83   32.97   32.99   32.38
   31.35   31.32   31.29    29.4   29.37   29.34   31.45   31.47   31.47   31.48
   31.49    31.5   31.52   31.53   31.53   31.54   29.76   32.79   32.82   32.83
   32.97   32.97   32.97   33.34   33.65   33.35   32.92   32.67   32.54   32.09
   32.06   30.51   30.86    30.6   30.21   30.99   29.99   29.91   32.82   33.96
Abutment Skew #Up #Dn= , 2 , 2
    4978  4987.8
   31.59   26.85
    4978  4987.8
   31.45   26.71
Abutment Skew #Up #Dn= , 2 , 2
  5012.3 5019.59
   26.64   31.68
  5012.3 5019.59
    26.5   31.54
BR Coef= 1 , 1 , 0 ,1.25, 0 ,,,0.8,0,2,0,
WSPro=,,,, 1 ,,,, 0 ,,,, 0 ,,,,-1 ,-1 ,-1 , 0 , 0 , 0 , 0 , 0
BR U #Sta/Elev= 60
  3384.2   34.88    3486   34.62  3507.7   34.57  3824.2   33.76  3899.9   33.18
  4009.9   33.97  4013.6   33.91  4069.9   33.05  4089.9   32.49  4347.7   32.97
  4572.6   32.88  4748.3   32.06  4776.8   31.93  4815.9   32.01    4825   32.03
  4841.3   32.57  4889.1   32.97  4905.9   33.11    4962   33.13  4966.9   32.52
 4970.69   31.49  4970.8   31.46 4970.91   31.43  4977.9   29.54    4978   29.51
 4978.11   29.48  4978.2   29.45  4987.7   26.88  4987.8   26.85  4991.4   25.59
  4996.5   24.81    5002   24.54  5008.1   26.23  5012.2   26.63  5012.3   26.64
 5019.39   29.85  5019.5    29.9  5026.2   32.93  5027.8   32.96  5027.9   32.97
 5034.39   33.11  5034.5   33.11 5034.61   33.11  5051.5   33.48    5102   33.79
  5133.7   33.49    5178   33.06  5214.9   32.81  5234.9   32.68  5298.1   32.23
  5303.9    32.2  5661.9   30.65  5921.9      31  5941.9   30.74  6111.9   30.35
  6131.9   31.13  6561.9   30.13  6631.9   30.05  6691.9   32.96  6883.2    34.1
BR U #Mann= 4
  3384.2      .2    3486      .1  4966.9     .04  5026.2      .1
BR U Banks=4966.9,5026.2
BR D #Sta/Elev= 60
  3384.2   34.74    3486   34.48  3507.7   34.43  3824.2   33.62  3899.9   33.04
  4009.9   33.83  4013.6   33.77  4069.9   32.91  4089.9   32.35  4347.7   32.83
  4572.6   32.74  4748.3   31.92  4776.8   31.79  4815.9   31.87    4825   31.89
  4841.3   32.43  4889.1   32.83  4905.9   32.97    4962   32.99  4966.9   32.38
 4970.69   31.35  4970.8   31.32 4970.91   31.29  4977.9    29.4    4978   29.37
 4978.11   29.34  4978.2   29.31  4987.7   26.74  4987.8   26.71  4991.4   25.45
  4996.5   24.67    5002    24.4  5008.1   26.09  5012.2   26.49  5012.3    26.5
 5019.39   29.71  5019.5   29.76  5026.2   32.79  5027.8   32.82  5027.9   32.83
 5034.39   32.97  5034.5   32.97 5034.61   32.97  5051.5   33.34    5102   33.65
  5133.7   33.35    5178   32.92  5214.9   32.67  5234.9   32.54  5298.1   32.09
  5303.9   32.06  5661.9   30.51  5921.9   30.86  5941.9    30.6  6111.9   30.21
  6131.9   30.99  6561.9   29.99  6631.9   29.91  6691.9   32.82  6883.2   33.96
BR D #Mann= 4
  3384.2      .2    3486      .1  4966.9     .04  5026.2      .1
BR D Banks=4966.9,5026.2
BC Design=,, 0 ,, 0 ,,,,,,
BC HTab HWMax=34.89
BC Use User HTab Curves=0
BC User HTab FreeFlow(D)= 0

Type RM Length L Ch R = 1 ,8665.0  ,356.1,356.1,356.1
BEGIN DESCRIPTION:
Downstream Section of Bridge/Culvert/Weir
END DESCRIPTION:
XS GIS Cut Line= 6
      3158631.13     13803969.55      3159222.46     13804185.18
      3159979.26     13804819.81      3160299.69     13805102.63
      3160749.61     13805498.37      3161557.23     13805780.01
#Sta/Elev= 30
  3384.2   34.76    3486    34.5  3824.2   33.64  3899.9   33.06  4009.9   33.85
  4089.9   32.37  4347.7   32.85  4572.6   32.76  4776.8   31.81    4825   31.91
  4841.3   32.45  4905.9   32.99    4962   33.01  4966.9    32.4  4991.4   25.47
  4996.5   24.69    5002   24.42  5008.1   26.11  5012.3   26.52  5026.2   32.81
  5051.5   33.36    5102   33.67  5298.1   32.11  5661.9   30.53  5921.9   30.88
  6111.9   30.23  6131.9   31.01  6631.9   29.93  6691.9   32.84  6883.2   33.98
#Mann= 4 , 1 , 0
  3384.2      .2       0    3486      .1       0  4966.9     .04       0
  5026.2      .1       0
#XS Ineff= 2 , 0
       0  4967.8    32.6  5020.7       0    30.4
Permanent Ineff=
       F       F
Bank Sta=4966.9,5026.2
XS Rating Curve= 0 ,0
Exp/Cntr=0.5,0.3

Type RM Length L Ch R = 1 ,8308.9  ,254.6,249.5,175.1
BEGIN DESCRIPTION:
Cross Section 8308.9-Interpolated
END DESCRIPTION:
XS GIS Cut Line= 6
      3159105.23     13804658.66      3159605.02     13804794.97
      3159966.88     13805060.71      3160142.16     13805100.29
      3160831.95     13805445.18      3161776.17     13805671.35
#Sta/Elev= 30
  4176.8    35.4  4286.8    35.4  4576.8    34.5  4616.8      33  4626.8    32.3
  4694.9    32.8  4854.9    32.8  4924.9    33.6  4954.9    32.6  4964.9    31.6
 4984.91   30.73 4998.03   25.83 4999.51    25.4 5000.25   25.12 5001.15    25.3
 5002.05   25.65 5025.01   30.91  5044.9    33.5  5124.9    32.5  5143.8      32
  5193.8    32.5  5203.8    31.9  5323.5    32.4  5544.7    32.6  6096.4    30.9
  6726.4    29.9  6746.4    29.7  6836.4    31.3  6876.4      33  7067.3    33.6
#Mann= 4 , 1 , 0
  4176.8      .1       0 4984.91     .04       0 5025.01      .1       0
  7067.3      .2       0
Bank Sta=4984.91,5025.01
XS Rating Curve= 0 ,0
Exp/Cntr=0.3,0.1

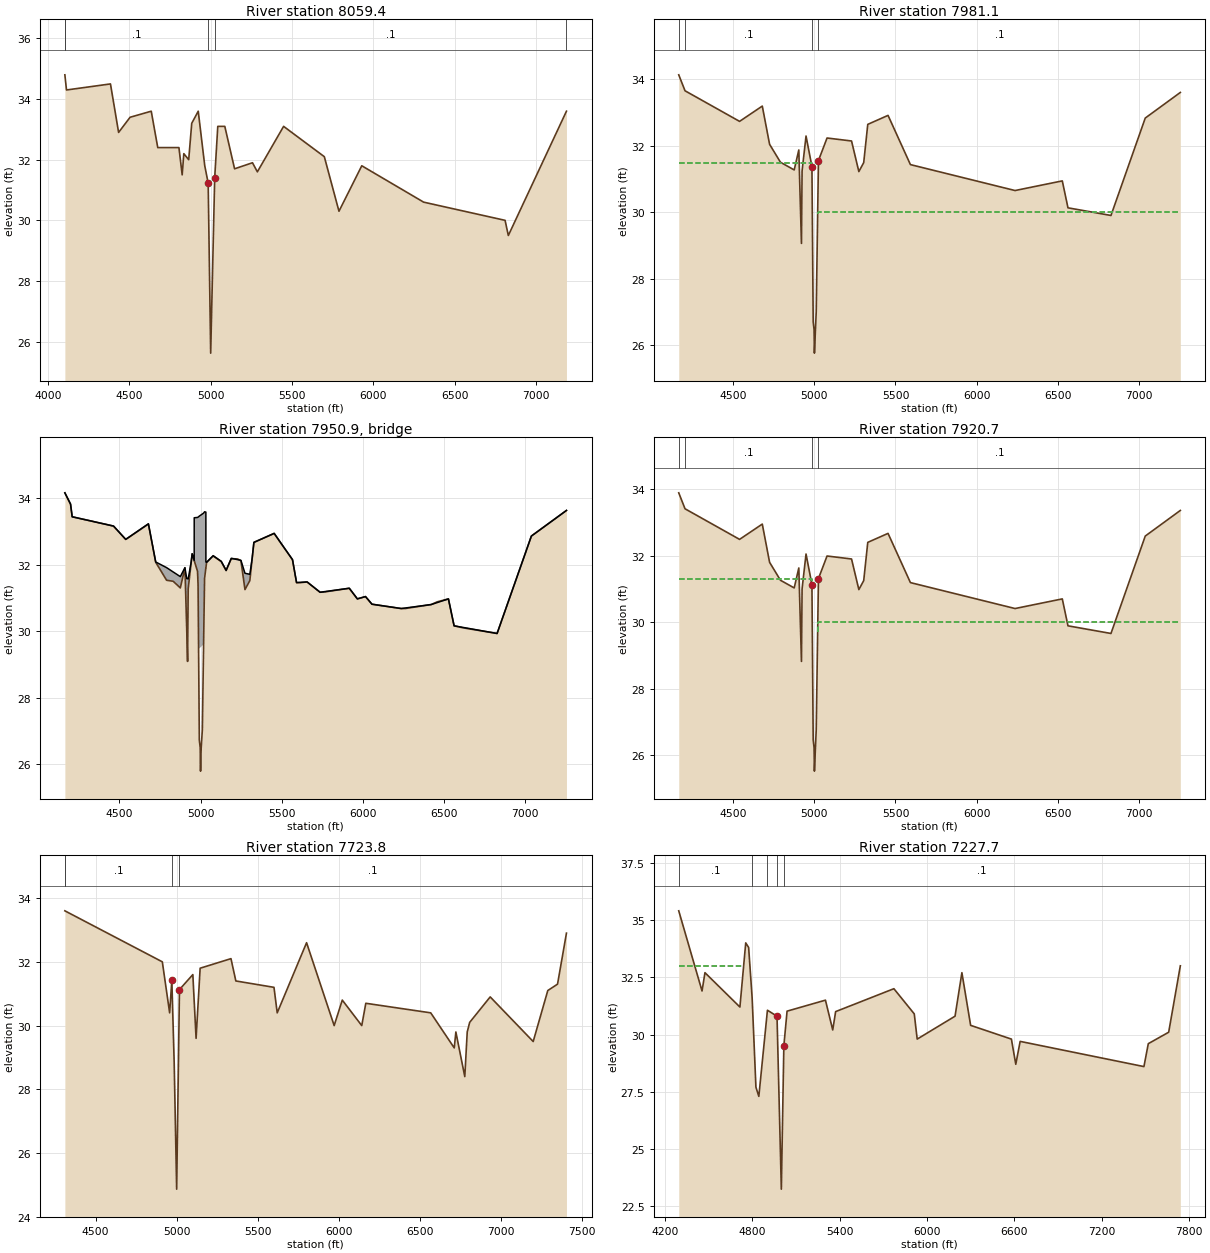
Type RM Length L Ch R = 1 ,8059.4  ,73.8,78.3,76.6
BEGIN DESCRIPTION:
Cross Section 8059.4-Interpolated
END DESCRIPTION:
XS GIS Cut Line= 6
      3158806.72     13805063.33       3159207.1     13805069.05
       3159584.6     13805097.65      3159756.19     13805206.32
      3160070.77     13805383.63      3161780.95     13805686.77
#Sta/Elev= 30
  4104.9    34.8  4114.9    34.3  4384.9    34.5  4434.9    32.9  4505.3    33.4
  4635.3    33.6  4675.3    32.4  4805.3    32.4  4825.3    31.5  4835.3    32.2
  4865.3      32  4883.9    33.2  4923.9    33.6  4963.9    31.8 4984.91   31.23
 5000.25   25.62 5025.01   31.41  5043.9    33.1    5087    33.1    5147    31.7
    5257    31.9    5287    31.6  5448.1    33.1  5698.1    32.1  5788.1    30.3
  5928.1    31.8  6308.1    30.6  6808.1      30  6828.1    29.5    7185    33.6
#Mann= 5 , 1 , 0
  4104.9      .2       0  4104.9      .1       0 4984.91     .04       0
 5025.01      .1       0    7185      .2       0
Bank Sta=4984.91,5025.01
XS Rating Curve= 0 ,0
Exp/Cntr=0.5,0.3

Type RM Length L Ch R = 1 ,7981.1  ,60.4,60.4,60.4
BEGIN DESCRIPTION:
Upstream Section of Bridge/Culvert/Weir
END DESCRIPTION:
XS GIS Cut Line= 6
      3158794.13     13805180.41      3159670.94     13805228.19
      3159796.57     13805312.96      3160224.06     13805690.05
      3161059.73     13805763.24      3161711.38     13805761.85
#Sta/Elev= 30
  4163.9   34.14  4202.7   33.66  4538.9   32.74  4678.9    33.2  4723.9   32.05
 4791.06   31.51 4875.61   31.28 4903.98   31.88  4920.3   29.07 4924.15   31.25
  4948.5    32.3 4984.91   31.38  4992.7   26.71 4998.03   26.48 5000.25   25.77
  5011.4   27.02 5025.01   31.56 5078.06   32.24  5229.1   32.15  5274.1   31.23
  5304.1    31.5  5329.1   32.65  5454.1   32.92    5592   31.44    6237   30.66
  6528.2   30.95  6563.2   30.14  6828.2   29.91  7039.6   32.84  7255.8   33.61
#Mann= 4 , 1 , 0
  4163.9      .2       0  4202.7      .1       0 4984.91     .04       0
 5025.01      .1       0
#XS Ineff= 2 , 0
       0    4984    31.5  5020.2       0      30
Permanent Ineff=
       F       F
Bank Sta=4984.91,5025.01
XS Rating Curve= 0 ,0
Exp/Cntr=0.5,0.3

Type RM Length L Ch R = 3 ,7950.9  ,,,
BEGIN DESCRIPTION:
INDIANA STREET, SKEW ANGLE OF 35 DEGREES
Structure ID: C63-10
END DESCRIPTION:
Bridge Culvert--1,0,-1,-1, 0
Deck Dist Width WeirC Skew NumUp NumDn MinLoCord MaxHiCord MaxSubmerge Is_Ogee
10,40.4,2.6,0, 52, 52, , , 0.95, 0, 1,1,,
  4163.9  4198.9  4208.9  4463.9  4538.9  4678.9  4723.9 4791.06 4831.49 4875.61
 4903.98 4915.13  4920.3 4924.15 4943.09  4948.5 4961.09  4961.2 4981.63 4984.91
 4988.11  4992.7 5019.06 5025.01 5033.11 5033.22 5037.15 5078.06    5128 5157.93
 5189.67  5249.1  5274.1  5304.1  5318.4  5329.1  5454.1    5567    5592    5657
    5737    5917    5967    6017    6057    6237    6422  6528.2  6563.2  6828.2
  7039.6  7255.8
   34.16   33.82   33.44   33.16   32.76   33.23   32.08   31.91   31.78   31.64
   31.91   31.58   31.58   31.57    32.1   32.33   32.13   33.41   33.42   33.43
   33.44   33.46   33.55   33.59   33.58   32.08   32.07   32.27    32.1   31.83
   32.19   32.13   31.74   31.71   32.19   32.67   32.94   32.15   31.46   31.48
   31.17   31.29   30.97   31.04   30.81   30.68    30.8   30.97   30.16   29.93
   32.86   33.63
   34.16   33.82   33.44   33.16   32.76   33.22   32.07   31.53    31.5    31.3
    31.9   30.04   29.09   31.27   32.09   32.32   32.12   32.12    31.8    31.4
   29.48   29.48    29.6   31.58    31.9    31.9   32.06   32.26   32.09   31.82
   32.18   32.12   31.25   31.52   32.18   32.67   32.94   32.15   31.46   31.48
   31.17   31.29   30.97   31.04   30.81   30.68    30.8   30.97   30.16   29.93
   32.86   33.63
  4163.9  4198.9  4208.9  4463.9  4538.9  4678.9  4723.9 4791.06 4831.49 4875.61
 4903.98 4915.13  4920.3 4924.15 4943.09  4948.5 4961.09  4961.2 4981.63 4984.91
 4988.11  4992.7 5019.06 5025.01 5033.11 5033.22 5037.15 5078.06    5128 5157.93
 5189.67  5249.1  5274.1  5304.1  5318.4  5329.1  5454.1    5567    5592    5657
    5737    5917    5967    6017    6057    6237    6422  6528.2  6563.2  6828.2
  7039.6  7255.8
   34.16   33.82   33.44   33.16   32.76   33.23   32.08   31.91   31.78   31.64
   31.91   31.58   31.58   31.57    32.1   32.33   32.13   33.41   33.42   33.43
   33.44   33.46   33.55   33.59   33.58   32.08   32.07   32.27    32.1   31.83
   32.19   32.13   31.74   31.71   32.19   32.67   32.94   32.15   31.46   31.48
   31.17   31.29   30.97   31.04   30.81   30.68    30.8   30.97   30.16   29.93
   32.86   33.63
   33.92   33.58    33.2   32.92   32.52   32.98   31.83   31.29   31.26   31.06
   31.66    29.8   28.85   31.03   31.85   32.08   31.88   31.88   31.56   31.16
   29.24   29.24   29.36   31.34   31.66   31.66   31.82   32.02   31.85   31.58
   31.94   31.88   31.01   31.28   31.94   32.43    32.7   31.91   31.22   31.24
   30.93   31.05   30.73    30.8   30.57   30.44   30.56   30.73   29.92   29.69
   32.62   33.39
Abutment Skew #Up #Dn= , 2 , 2
 4987.91  4992.7
   29.48   26.73
 4987.91  4992.7
   29.24   26.49
Abutment Skew #Up #Dn= , 2 , 2
  5011.4 5019.26
   27.04    29.6
  5011.4 5019.26
    26.8   29.36
BR Coef= 1 , 1 , 0 ,1.25, 0 ,,,0.8,0,2,0,
WSPro=,,,, 1 ,,,, 0 ,,,, 0 ,,,,-1 ,-1 ,-1 , 0 , 0 , 0 , 0 , 0
BR U #Sta/Elev= 84
  4163.9   34.16  4198.9   33.82  4202.7   33.68  4208.9   33.44  4463.9   33.16
  4538.9   32.76  4552.1    32.8  4678.9   33.22  4723.9   32.07 4791.06   31.53
 4791.64   31.53 4831.49    31.5 4875.61    31.3 4876.51   31.32 4903.98    31.9
 4915.13   30.04  4920.3   29.09 4924.15   31.27 4925.05   31.31 4943.09   32.09
  4948.5   32.32 4961.09   32.12  4961.2   32.12  4961.3   32.12 4970.07   31.98
 4981.63    31.8 4984.91    31.4 4988.02   29.54 4988.11   29.48  4992.6   26.79
  4992.7   26.73 4998.03    26.5 4999.51   26.07 5000.25   25.79 5001.15   25.97
 5002.05   26.32  5011.3   27.03  5011.4   27.04 5019.06    29.6 5019.17   29.63
 5019.27   29.67 5024.93   31.55 5025.01   31.58    5033    31.9 5033.11    31.9
 5033.22    31.9 5037.15   32.06 5058.96   32.17 5078.06   32.26 5098.89   32.19
    5128   32.09 5157.93   31.82 5169.08   31.95 5189.67   32.18  5194.7   32.18
  5195.2   32.18  5229.1   32.17  5249.1   32.12  5274.1   31.25  5304.1   31.52
  5318.4   32.18  5329.1   32.67  5454.1   32.94    5502    32.6    5567   32.15
    5592   31.46    5617   31.46    5657   31.48    5737   31.17    5767   31.18
    5917   31.29    5967   30.97    6017   31.04    6057   30.81    6237   30.68
    6262   30.68    6422    30.8  6458.2   30.88  6528.2   30.97  6563.2   30.16
  6618.2    30.1  6828.2   29.93  7039.6   32.86  7255.8   33.63
BR U #Mann= 4
  4163.9      .2  4202.7      .1 4984.91     .04 5025.01      .1
BR U Banks=4984.91,5025.01
BR D #Sta/Elev= 84
  4163.9   33.92  4198.9   33.58  4202.7   33.44  4208.9    33.2  4463.9   32.92
  4538.9   32.52  4552.1   32.56  4678.9   32.98  4723.9   31.83 4791.06   31.29
 4791.64   31.29 4831.49   31.26 4875.61   31.06 4876.51   31.08 4903.98   31.66
 4915.13    29.8  4920.3   28.85 4924.15   31.03 4925.05   31.07 4943.09   31.85
  4948.5   32.08 4961.09   31.88  4961.2   31.88  4961.3   31.88 4970.07   31.74
 4981.63   31.56 4984.91   31.16 4988.02    29.3 4988.11   29.24  4992.6   26.55
  4992.7   26.49 4998.03   26.26 4999.51   25.83 5000.25   25.55 5001.15   25.73
 5002.05   26.08  5011.3   26.79  5011.4    26.8 5019.06   29.36 5019.17   29.39
 5019.27   29.43 5024.93   31.31 5025.01   31.34    5033   31.66 5033.11   31.66
 5033.22   31.66 5037.15   31.82 5058.96   31.93 5078.06   32.02 5098.89   31.95
    5128   31.85 5157.93   31.58 5169.08   31.71 5189.67   31.94  5194.7   31.94
  5195.2   31.94  5229.1   31.93  5249.1   31.88  5274.1   31.01  5304.1   31.28
  5318.4   31.94  5329.1   32.43  5454.1    32.7    5502   32.36    5567   31.91
    5592   31.22    5617   31.22    5657   31.24    5737   30.93    5767   30.94
    5917   31.05    5967   30.73    6017    30.8    6057   30.57    6237   30.44
    6262   30.44    6422   30.56  6458.2   30.64  6528.2   30.73  6563.2   29.92
  6618.2   29.86  6828.2   29.69  7039.6   32.62  7255.8   33.39
BR D #Mann= 4
  4163.9      .2  4202.7      .1 4984.91     .04 5025.01      .1
BR D Banks=4984.91,5025.01
BC Design=,, 0 ,, 0 ,,,,,,
BC HTab HWMax=34.14
BC Use User HTab Curves=0
BC User HTab FreeFlow(D)= 0

Type RM Length L Ch R = 1 ,7920.7  ,196.9,196.9,196.9
BEGIN DESCRIPTION:
Downstream Section of Bridge/Culvert/Weir
END DESCRIPTION:
XS GIS Cut Line= 6
      3158753.39       13805225.       3159630.2     13805272.79
      3159755.83     13805357.56      3160183.32     13805734.65
      3161018.99     13805807.84      3161670.64     13805806.44
#Sta/Elev= 30
  4163.9   33.89  4202.7   33.41  4538.9   32.49  4678.9   32.95  4723.9    31.8
 4791.06   31.26 4875.61   31.03 4903.98   31.63  4920.3   28.82 4924.15      31
  4948.5   32.05 4984.91   31.13  4992.7   26.46 4998.03   26.23 5000.25   25.52
  5011.4   26.77 5025.01   31.31 5078.06   31.99  5229.1    31.9  5274.1   30.98
  5304.1   31.25  5329.1    32.4  5454.1   32.67    5592   31.19    6237   30.41
  6528.2    30.7  6563.2   29.89  6828.2   29.66  7039.6   32.59  7255.8   33.36
#Mann= 4 , 1 , 0
  4163.9      .2       0  4202.7      .1       0 4984.91     .04       0
 5025.01      .1       0
#XS Ineff= 2 , 0
       0    4984    31.3  5020.2       0      30
Permanent Ineff=
       F       F
Bank Sta=4984.91,5025.01
XS Rating Curve= 0 ,0
Exp/Cntr=0.5,0.3

Type RM Length L Ch R = 1 ,7723.8  ,496.9,496.1,131.6
BEGIN DESCRIPTION:
Cross Section 7723.8-Interpolated
END DESCRIPTION:
XS GIS Cut Line= 6
      3158846.76     13805446.55      3159447.33     13805446.55
      3159630.36     13805446.55      3160219.48     13805835.48
      3161347.05     13805929.88       3161813.7     13805874.11
#Sta/Elev= 30
  4311.2    33.6  4911.8      32  4956.8    30.4  4970.4   31.42  4984.9   28.82
  5000.1   24.87  5017.4   31.13  5099.8    31.6  5119.8    29.6  5144.8    31.8
  5334.8    32.1  5364.8    31.4  5599.8    31.2  5619.8    30.4  5800.7    32.6
  5970.7      30  6020.7    30.8  6140.7      30  6165.7    30.7  6565.7    30.4
  6710.7    29.3  6720.7    29.8  6775.7    28.4  6790.7    29.8  6805.7    30.1
  6932.2    30.9  7197.2    29.5  7287.2    31.1  7347.2    31.3  7402.2    32.9
#Mann= 4 , 1 , 0
  4311.2      .2       0  4311.2      .1       0  4970.4     .04       0
  5017.4      .1       0
Bank Sta=4970.4,5017.4
XS Rating Curve= 0 ,0
Exp/Cntr=0.3,0.1

Type RM Length L Ch R = 1 ,7227.7  ,975.9,978.5,729
BEGIN DESCRIPTION:
Cross Section 7227.7
END DESCRIPTION:
XS GIS Cut Line= 4
      3158815.95     13805931.15      3159523.28     13805942.52
      3160759.07      13805995.2      3162255.89     13806093.86
#Sta/Elev= 30
  4295.6    35.4  4455.6    31.9  4475.6    32.7  4715.6    31.2  4755.6      34
  4775.6    33.8  4799.6    31.6  4825.6    27.7  4845.6    27.3  4904.6   31.06
  4970.4    30.8  5000.1   23.25  5017.4   29.51  5039.5   31.02    5303    31.5
    5353    30.2    5373      31    5773      32    5913    30.9    5933    29.8
    6193    30.8    6240    32.7    6300    30.4    6580    29.8    6610    28.7
    6640    29.7    7490    28.6    7520    29.6    7660    30.1    7740      33
#Mann= 5 , 1 , 0
  4295.6      .1       0  4799.6     .99       0  4904.6      .1       0
  4970.4     .04       0  5017.4      .1       0
#XS Ineff= 2 , 0
       0  4741.3      33               0
Permanent Ineff=
       F       F
Bank Sta=4970.4,5017.4
XS Rating Curve= 0 ,0
Exp/Cntr=0.3,0.1