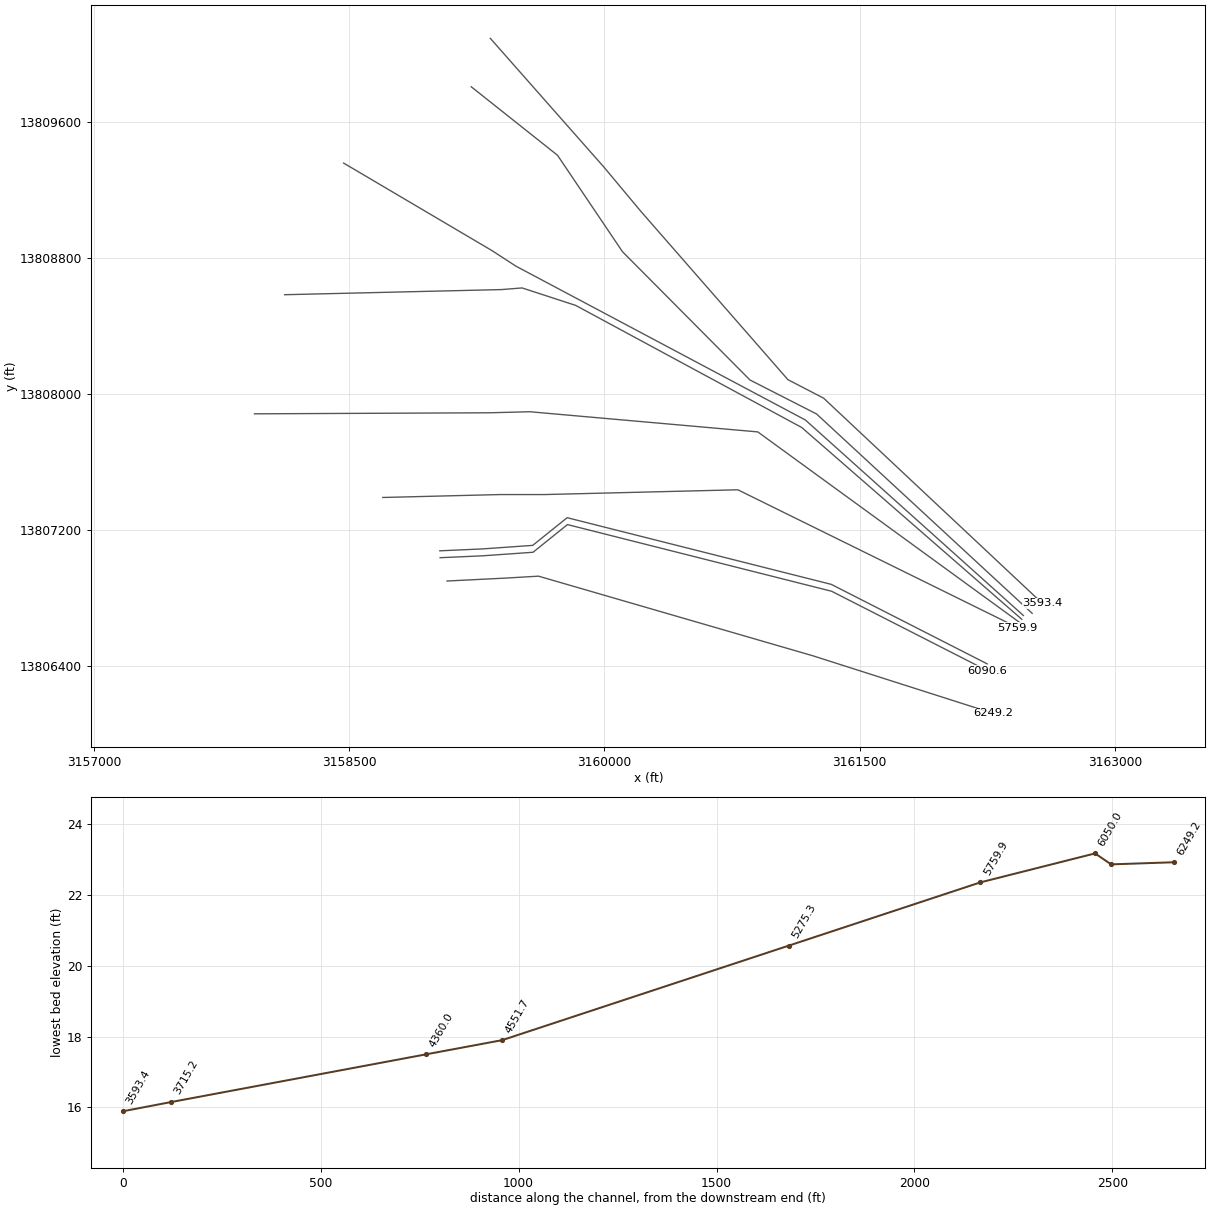
HEC-RAS study C106-03-00.PRJ: C106-03-00

--- C106-03-00.g01 (geometry) --- (continued)

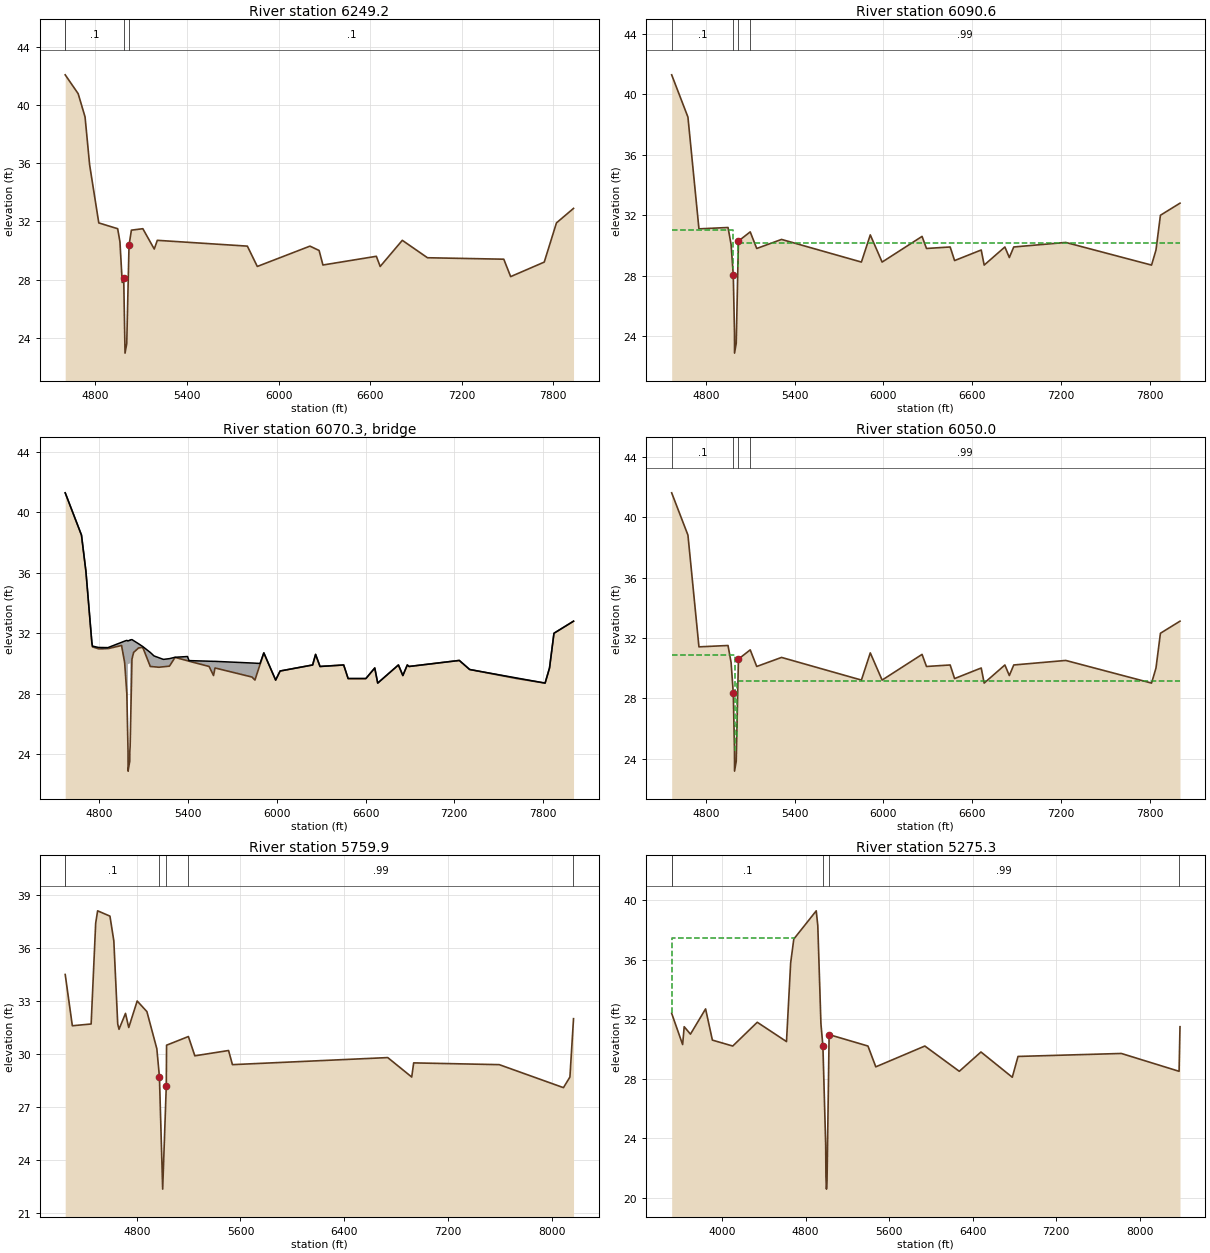
Type RM Length L Ch R = 1 ,6249.2  ,128.2,158.6,198.9
BEGIN DESCRIPTION:
Cross Section 6249.2-Interpolated
END DESCRIPTION:
XS GIS Cut Line= 5
      3159075.55     13806899.34      3159418.73      13806916.5
       3159613.2     13806927.94      3161226.14     13806458.93
      3162285.18     13806120.03
#Sta/Elev= 30
  4602.5    42.1  4687.5    40.8  4732.5    39.2  4762.5    35.9  4822.5    31.9
  4946.1    31.5  4961.1    30.6  4976.1    27.8  4985.8   28.08  4994.5   22.93
  5005.6   23.58  5020.6   30.35  5036.1    31.4  5111.1    31.5  5185.9    30.1
  5205.9    30.7  5795.9    30.3  5860.9    28.9  6205.9    30.3  6265.9      30
  6290.9      29  6640.9    29.6  6665.9    28.9  6810.9    30.7  6975.7    29.5
  7475.7    29.4  7520.7    28.2  7740.7    29.2  7820.7    31.9  7932.6    32.9
#Mann= 4 , 1 , 0
  4602.5      .2       0  4602.5      .1       0  4985.8     .04       0
  5020.6      .1       0
Bank Sta=4985.8,5020.6
XS Rating Curve= 0 ,0
Exp/Cntr=0.5,0.3

Type RM Length L Ch R = 1 ,6090.6  ,40.6,40.6,40.6
BEGIN DESCRIPTION:
Upstream Section of Bridge/Culvert/Weir
END DESCRIPTION:
XS GIS Cut Line= 6
      3159035.08     13807036.61      3159284.35      13807047.7
      3159581.06     13807068.66      3159783.42     13807231.62
      3161335.75     13806839.02      3162251.83     13806371.02
#Sta/Elev= 30
  4569.2    41.3  4679.2    38.5  4753.6    31.1  4950.2   31.19    4971   30.06
  4985.8   28.02    4994   24.18  4994.3   22.87  5005.6   23.52  5020.6   30.29
  5100.2    30.9  5144.3    29.8    5312    30.4    5852    28.9    5912    30.7
    5992    28.9    6262    30.6    6292    29.8    6452    29.9    6482      29
    6662    29.7    6682    28.7    6822    29.9    6852    29.2    6882    29.9
  7233.6    30.2  7813.6    28.7  7843.6    29.7  7873.6      32  8005.9    32.8
#Mann= 4 ,-1 , 0
  4569.2      .1       0  4985.8     .04       0  5020.6      .1       0
  5100.2     .99       0
#XS Ineff= 2 , 0
       0  4982.7      31  5016.8       0   30.14
Permanent Ineff=
       F       F
Bank Sta=4985.8,5020.6
XS Rating Curve= 0 ,0
Exp/Cntr=0.5,0.3

Type RM Length L Ch R = 3 ,6070.3  ,,,
BEGIN DESCRIPTION:
MICHIGAN AVENUE
Structure ID: C63-9
END DESCRIPTION:
Bridge Culvert--1,0,-1,-1, 0
Deck Dist Width WeirC Skew NumUp NumDn MinLoCord MaxHiCord MaxSubmerge Is_Ogee
10,20.6,2.6,0, 52, 52, , , 0.95, 0, 1,1,,
  4569.2  4679.2  4709.2  4749.2  4753.2  4794.9  4858.1  4950.2    4971  4985.8
 4993.11  4993.2 5008.99  5009.1  5020.6  5031.8  5064.4  5093.5  5144.3  5169.5
  5232.9  5273.9    5312  5396.2  5406.2    5542    5572    5582    5832    5852
  5886.3    5912    5992    6022    6242    6262    6292    6452    6482    6602
    6662    6682    6822    6852    6882  6893.6  7233.6  7303.6  7813.6  7843.6
  7873.6  8005.9
    41.3    38.5    36.1    31.4   31.15   31.06   31.05    31.4   31.48   31.53
   31.49   31.49   31.55   31.56   31.58   31.51   31.31   31.12   30.73    30.5
   30.27   30.32   30.41   30.46   30.19   30.15   30.14   30.14   30.03   30.02
      30    30.7    28.9    29.5    29.9    30.6    29.8    29.9      29      29
    29.7    28.7    29.9    29.2    29.9    29.8    30.2    29.6    28.7    29.7
      32    32.8
    41.3    38.5    36.1    31.4   31.13   30.97   30.99   31.19   30.06   28.02
    24.6   29.95   30.01   24.94   30.29   30.73   31.02   31.07    29.8   29.78
   29.78   29.82    30.4   30.18   30.15    29.8    29.2    29.7    29.1    28.9
   29.93    30.7    28.9    29.5    29.9    30.6    29.8    29.9      29      29
    29.7    28.7    29.9    29.2    29.9    29.8    30.2    29.6    28.7    29.7
      32    32.8
  4569.2  4679.2  4709.2  4749.2  4753.2  4794.9  4858.1  4950.2    4971  4985.8
 4993.11  4993.2 5008.99  5009.1  5020.6  5031.8  5064.4  5093.5  5144.3  5169.5
  5232.9  5273.9    5312  5396.2  5406.2    5542    5572    5582    5832    5852
  5886.3    5912    5992    6022    6242    6262    6292    6452    6482    6602
    6662    6682    6822    6852    6882  6893.6  7233.6  7303.6  7813.6  7843.6
  7873.6  8005.9
    41.3    38.5    36.1    31.4   31.15   31.06   31.05    31.4   31.48   31.53
   31.49   31.49   31.55   31.56   31.58   31.51   31.31   31.12   30.73    30.5
   30.27   30.32   30.41   30.46   30.19   30.15   30.14   30.14   30.03   30.02
      30    30.7    28.9    29.5    29.9    30.6    29.8    29.9      29      29
    29.7    28.7    29.9    29.2    29.9    29.8    30.2    29.6    28.7    29.7
      32    32.8
   41.21   38.41   36.01   31.31   31.04   30.88    30.9    31.1   29.97   27.93
   24.51   29.86   29.92   24.85    30.2   30.64   30.93   30.98   29.71   29.69
   29.69   29.73   30.31   30.09   30.06   29.71   29.11   29.61   29.01   28.81
   29.84   30.61   28.81   29.41   29.81   30.51   29.71   29.81   28.91   28.91
   29.61   28.61   29.81   29.11   29.81   29.71   30.11   29.51   28.61   29.61
   31.91   32.71
Abutment Skew #Up #Dn= , 2 , 2
    4993  4994.1
   29.95   23.74
    4993  4994.1
   29.86   23.65
Abutment Skew #Up #Dn= , 2 , 2
  5008.1 5009.19
   24.48   30.01
  5008.1 5009.19
   24.39   29.92
BR Coef= 1 , 1 , 0 ,1.25, 0 ,,,0.8,-1,2,0,
WSPro=,,,, 1 ,,,, 0 ,,,, 0 ,,,,-1 ,-1 ,-1 , 0 , 0 , 0 , 0 , 0
BR U #Sta/Elev= 80
  4569.2    41.3  4679.2    38.5  4709.2    36.1  4749.2    31.4  4753.2   31.13
  4753.6    31.1  4794.9   30.97  4795.9   30.97  4821.8   30.97  4858.1   30.99
  4862.5   30.99  4950.2   31.19    4971   30.06  4984.9   28.14  4985.8   28.02
    4993   24.65 4993.11    24.6  4993.2   24.55    4994   24.18  4994.1   23.74
  4994.3   22.87 4994.39   22.88  4994.5   22.88 4994.61   22.89  5000.7   23.25
  5005.6   23.52    5006   24.18    5008   24.47  5008.1   24.48 5008.99   24.89
  5009.1   24.94 5010.19   25.45  5010.3    25.5 5010.41   25.55    5017   28.62
  5017.1   28.66  5020.6   30.29  5031.8   30.73  5064.4   31.02  5093.5   31.07
  5094.3   31.05  5100.2    30.9  5128.7   30.19  5144.3    29.8  5169.5   29.78
  5201.8   29.75  5232.9   29.78  5273.9   29.82    5312    30.4  5396.2   30.18
  5406.2   30.15    5542    29.8    5572    29.2    5582    29.7  5624.4    29.6
    5832    29.1    5852    28.9  5886.3   29.93    5912    30.7    5992    28.9
    6022    29.5    6242    29.9    6262    30.6    6292    29.8    6452    29.9
    6482      29    6602      29    6662    29.7    6682    28.7    6822    29.9
    6852    29.2    6882    29.9  6893.6    29.8  7233.6    30.2  7303.6    29.6
  7623.6      29  7813.6    28.7  7843.6    29.7  7873.6      32  8005.9    32.8
BR U #Mann= 4
  4569.2      .1  4985.8     .04  5020.6      .1  5100.2     .99
BR U Banks=4985.8,5020.6
BR D #Sta/Elev= 80
  4569.2   41.21  4679.2   38.41  4709.2   36.01  4749.2   31.31  4753.2   31.04
  4753.6   31.01  4794.9   30.88  4795.9   30.88  4821.8   30.88  4858.1    30.9
  4862.5    30.9  4950.2    31.1    4971   29.97  4984.9   28.05  4985.8   27.93
    4993   24.56 4993.11   24.51  4993.2   24.46    4994   24.09  4994.1   23.65
  4994.3   22.78 4994.39   22.79  4994.5   22.79 4994.61    22.8  5000.7   23.16
  5005.6   23.43    5006   24.09    5008   24.38  5008.1   24.39 5008.99    24.8
  5009.1   24.85 5010.19   25.36  5010.3   25.41 5010.41   25.46    5017   28.53
  5017.1   28.57  5020.6    30.2  5031.8   30.64  5064.4   30.93  5093.5   30.98
  5094.3   30.96  5100.2   30.81  5128.7    30.1  5144.3   29.71  5169.5   29.69
  5201.8   29.66  5232.9   29.69  5273.9   29.73    5312   30.31  5396.2   30.09
  5406.2   30.06    5542   29.71    5572   29.11    5582   29.61  5624.4   29.51
    5832   29.01    5852   28.81  5886.3   29.84    5912   30.61    5992   28.81
    6022   29.41    6242   29.81    6262   30.51    6292   29.71    6452   29.81
    6482   28.91    6602   28.91    6662   29.61    6682   28.61    6822   29.81
    6852   29.11    6882   29.81  6893.6   29.71  7233.6   30.11  7303.6   29.51
  7623.6   28.91  7813.6   28.61  7843.6   29.61  7873.6   31.91  8005.9   32.71
BR D #Mann= 4
  4569.2      .1  4985.8     .04  5020.6      .1  5100.2     .99
BR D Banks=4985.8,5020.6
BC Design=,, 0 ,, 0 ,,,,,,
BC HTab HWMax=41.3
BC Use User HTab Curves=0
BC User HTab FreeFlow(D)= 0

Type RM Length L Ch R = 1 ,6050.0  ,290.1,290.1,290.1
BEGIN DESCRIPTION:
Downstream Section of Bridge/Culvert/Weir
END DESCRIPTION:
XS GIS Cut Line= 6
      3159033.22     13807077.17      3159282.49     13807088.26
       3159579.2     13807109.22      3159781.56     13807272.18
      3161333.89     13806879.58      3162249.97     13806411.58
#Sta/Elev= 30
  4569.2   41.61  4679.2   38.81  4753.6   31.41  4950.2    31.5    4971   30.37
  4985.8   28.33    4994   24.49  4994.3   23.18  5005.6   23.83  5020.6    30.6
  5100.2   31.21  5144.3   30.11    5312   30.71    5852   29.21    5912   31.01
    5992   29.21    6262   30.91    6292   30.11    6452   30.21    6482   29.31
    6662   30.01    6682   29.01    6822   30.21    6852   29.51    6882   30.21
  7233.6   30.51  7813.6   29.01  7843.6   30.01  7873.6   32.31  8005.9   33.11
#Mann= 4 ,-1 , 0
  4569.2      .1       0  4985.8     .04       0  5020.6      .1       0
  5100.2     .99       0
#XS Ineff= 2 , 0
       0    4994    30.9 5009.19       0   29.17
Permanent Ineff=
       F       T
Bank Sta=4985.8,5020.6
XS Rating Curve= 0 ,0
Exp/Cntr=0.5,0.3

Type RM Length L Ch R = 1 ,5759.9  ,484.9,484.6,383.7
BEGIN DESCRIPTION:
Cross Section 5759.9-Interpolated
END DESCRIPTION:
XS GIS Cut Line= 5
      3158698.05     13807391.23      3159384.41     13807408.39
      3159647.52     13807408.39      3160784.68     13807436.51
      3162428.25      13806625.4
#Sta/Elev= 30
  4248.6    34.5  4303.6    31.6  4448.6    31.7  4483.6    37.4  4498.6    38.1
  4593.6    37.8  4623.6    36.4  4653.6    31.7  4663.6    31.4  4713.6    32.3
  4738.6    31.5  4803.6      33  4878.6    32.4  4955.2    30.3  4975.2   28.72
  5000.3   22.36  5028.1    28.2  5030.2    30.5  5198.6   30.99  5248.3    29.9
  5508.3    30.2  5538.3    29.4  6735.8    29.8  6920.8    28.7  6935.8    29.5
  7595.8    29.4  8090.8    28.1  8140.8    28.7  8164.7   31.54  8168.6      32
#Mann= 6 , 1 , 0
  4248.6      .2       0  4248.6      .1       0  4975.2     .04       0
  5028.1      .1       0  5198.6     .99       0  8164.7      .2       0
Bank Sta=4975.2,5028.1
XS Rating Curve= 0 ,0
Exp/Cntr=0.3,0.1

Type RM Length L Ch R = 1 ,5275.3  ,724.8,723.6,360.4
BEGIN DESCRIPTION:
Cross Section 5275.3-Intepolated
END DESCRIPTION:
XS GIS Cut Line= 6
      3157943.98      13807883.8      3159329.01     13807889.96
      3159562.93     13807896.11      3159644.16     13807888.76
      3160901.83     13807777.31       3162442.5      13806653.9
#Sta/Elev= 30
  3516.8    32.4  3621.8    30.3  3636.8    31.5  3696.8      31  3841.8    32.7
  3906.8    30.6  4101.8    30.2  4336.8    31.8  4616.8    30.5  4656.8    35.8
  4686.8    37.4  4901.8    39.3  4916.8    38.3  4946.8    31.7  4965.7   30.19
  4992.4   23.55  4994.6   21.42  4999.7   20.57  5005.1   21.07  5025.3   30.97
  5397.4    30.2  5472.4    28.8  5942.4    30.2  6272.4    28.5    6480    29.8
    6780    28.1    6835    29.5    7825    29.7    8378    28.5  8386.8    31.5
#Mann= 5 , 1 , 0
  3516.8      .2       0  3516.8      .1       0  4965.7     .04       0
  5025.3     .99       0    8378      .2       0
#XS Ineff= 2 , 0
       0    4689   37.44               0
Permanent Ineff=
       F       F
Bank Sta=4965.7,5025.3
XS Rating Curve= 0 ,0
Exp/Cntr=0.3,0.1

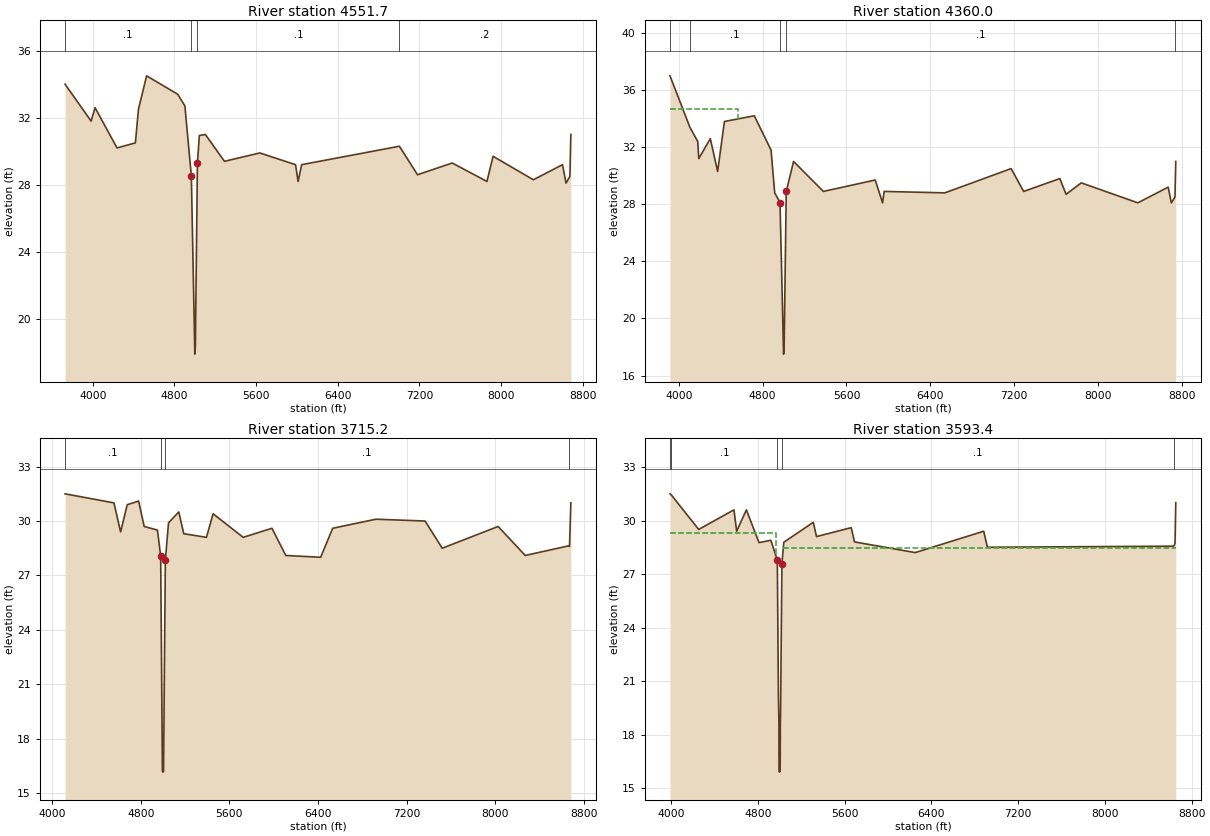
Type RM Length L Ch R = 1 ,4551.7  ,227,191.7,46.5
BEGIN DESCRIPTION:
Cross Section 4551.7
END DESCRIPTION:
XS GIS Cut Line= 6
      3158121.37      13808585.1      3159395.64     13808615.35
      3159516.79     13808625.04      3159831.93      13808522.1
        3161160.     13807803.37      3162453.42     13806673.95
#Sta/Elev= 30
  3728.6      34  3983.6    31.8  4022.4    32.6  4237.4    30.2  4417.4    30.5
  4447.4    32.5  4527.4    34.5  4832.4    33.4  4902.4    32.7  4965.7   28.52
  4999.7    17.9  5005.1    18.4  5025.3    29.3  5044.1   30.94  5103.3      31
  5289.9    29.4  5636.4    29.9  5986.4    29.2  6011.4    28.2  6046.4    29.2
  7003.9    30.3  7181.5    28.6  7521.5    29.3  7861.5    28.2  7921.5    29.7
  8316.5    28.3  8601.5    29.2  8636.5    28.1  8673.9    28.5  8683.6      31
#Mann= 4 , 1 , 0
  3728.6      .1       0  4965.7     .03       0  5025.3      .1       0
  7003.9      .2       0
Bank Sta=4965.7,5025.3
XS Rating Curve= 0 ,0
Exp/Cntr=0.3,0.1

Type RM Length L Ch R = 1 ,4360.0  ,669.4,644.8,150.4
BEGIN DESCRIPTION:
Cross Section 4360.0-Interpolated
END DESCRIPTION:
XS GIS Cut Line= 5
      3158468.03     13809360.15      3159339.75     13808844.84
      3159480.09     13808753.45       3161181.4     13807847.53
       3162462.6     13806696.38
#Sta/Elev= 30
    3915      37  4105.4   33.39    4180    32.4    4190    31.2    4300    32.6
    4370    30.3    4435    33.8    4720    34.2    4880    31.8    4915    28.8
  4965.7   28.12  4999.7    17.5  5005.1      18  5025.3    28.9  5095.1      31
  5380.1    28.9  5875.1    29.7  5945.1    28.1  5960.1    28.9  6540.1    28.8
  7172.6    30.5  7292.6    28.9  7637.6    29.8  7697.6    28.7  7842.6    29.5
  8382.6    28.1  8672.6    29.2  8702.6    28.1  8737.1    28.5    8745      31
#Mann= 5 , 1 , 0
    3915      .2       0  4105.4      .1       0  4965.7    .015       0
  5025.3      .1       0  8737.1      .2       0
#XS Ineff= 2 , 0
       0    4567    34.7               0
Permanent Ineff=
       F       F
Bank Sta=4965.7,5025.3
XS Rating Curve= 0 ,0
Exp/Cntr=0.3,0.1

Type RM Length L Ch R = 1 ,3715.2  ,92.6,121.8,154.8
BEGIN DESCRIPTION:
Cross Section 3715.2-Interpolated
END DESCRIPTION:
XS GIS Cut Line= 6
      3159218.01     13809809.37      3159724.87      13809406.2
      3160106.72     13808838.31      3160855.92     13808082.96
      3161247.35     13807882.86      3162514.09     13806709.28
#Sta/Elev= 30
    4115    31.5  4556.7      31  4616.7    29.4  4676.7    30.9  4779.7    31.1
  4829.7    29.7  4949.7    29.5  4978.7   28.07  4994.5    16.2  4998.8   16.15
  5004.6   16.19  5020.9   27.83  5049.7    29.9  5142.4    30.5  5187.4    29.3
  5392.4    29.1  5452.4    30.4  5724.3    29.1  5984.3    29.6  6109.3    28.1
  6424.3      28  6533.2    29.6  6923.2    30.1  7367.8      30  7522.8    28.5
  8027.8    29.7  8272.8    28.1  8664.9   28.63  8672.8    28.6    8685      31
#Mann= 4 , 1 , 0
    4115      .1       0  4978.7    .015       0  5020.9      .1       0
  8664.9      .2       0
Bank Sta=4978.7,5020.9
XS Rating Curve= 0 ,0
Exp/Cntr=0.5,0.3

Type RM Length L Ch R = 1 ,3593.4  ,51,51,51
BEGIN DESCRIPTION:
Upstream Section of Bridge/Culvert/Weir
END DESCRIPTION:
XS GIS Cut Line= 6
      3159329.95     13810094.66      3159998.18     13809335.77
      3160214.49      13809076.2      3161078.85     13808084.96
      3161288.53     13807976.08      3162574.23     13806767.64
#Sta/Elev= 30
  3988.8   31.52    4002   31.45  4253.8   29.52  4578.8   30.62  4603.8   29.42
  4693.3   30.62  4810.1   28.78  4919.1   28.91  4978.7   27.81  4988.9   20.21
  4994.1   18.42  4994.2   16.79  4994.5   15.94  4998.8   15.89  5004.6   15.93
  5005.7   16.91  5006.1   18.41    5009   19.42  5020.9   27.57  5038.4    28.8
  5310.5   29.92  5340.5   29.12  5660.5   29.62  5690.5   28.82  6250.5   28.22
  6882.4   29.42  6916.5   28.52  8634.2   28.58  8646.8   28.72  8653.8   31.02
#Mann= 5 , 1 , 0
  3988.8      .2       0    4002      .1       0  4978.7    .015       0
  5020.9      .1       0  8634.2      .2       0
#XS Ineff= 2 , 0
       0    4963    29.3    5034       0    28.5
Permanent Ineff=
       F       F
Bank Sta=4978.7,5020.9
XS Rating Curve= 0 ,0
Exp/Cntr=0.5,0.3