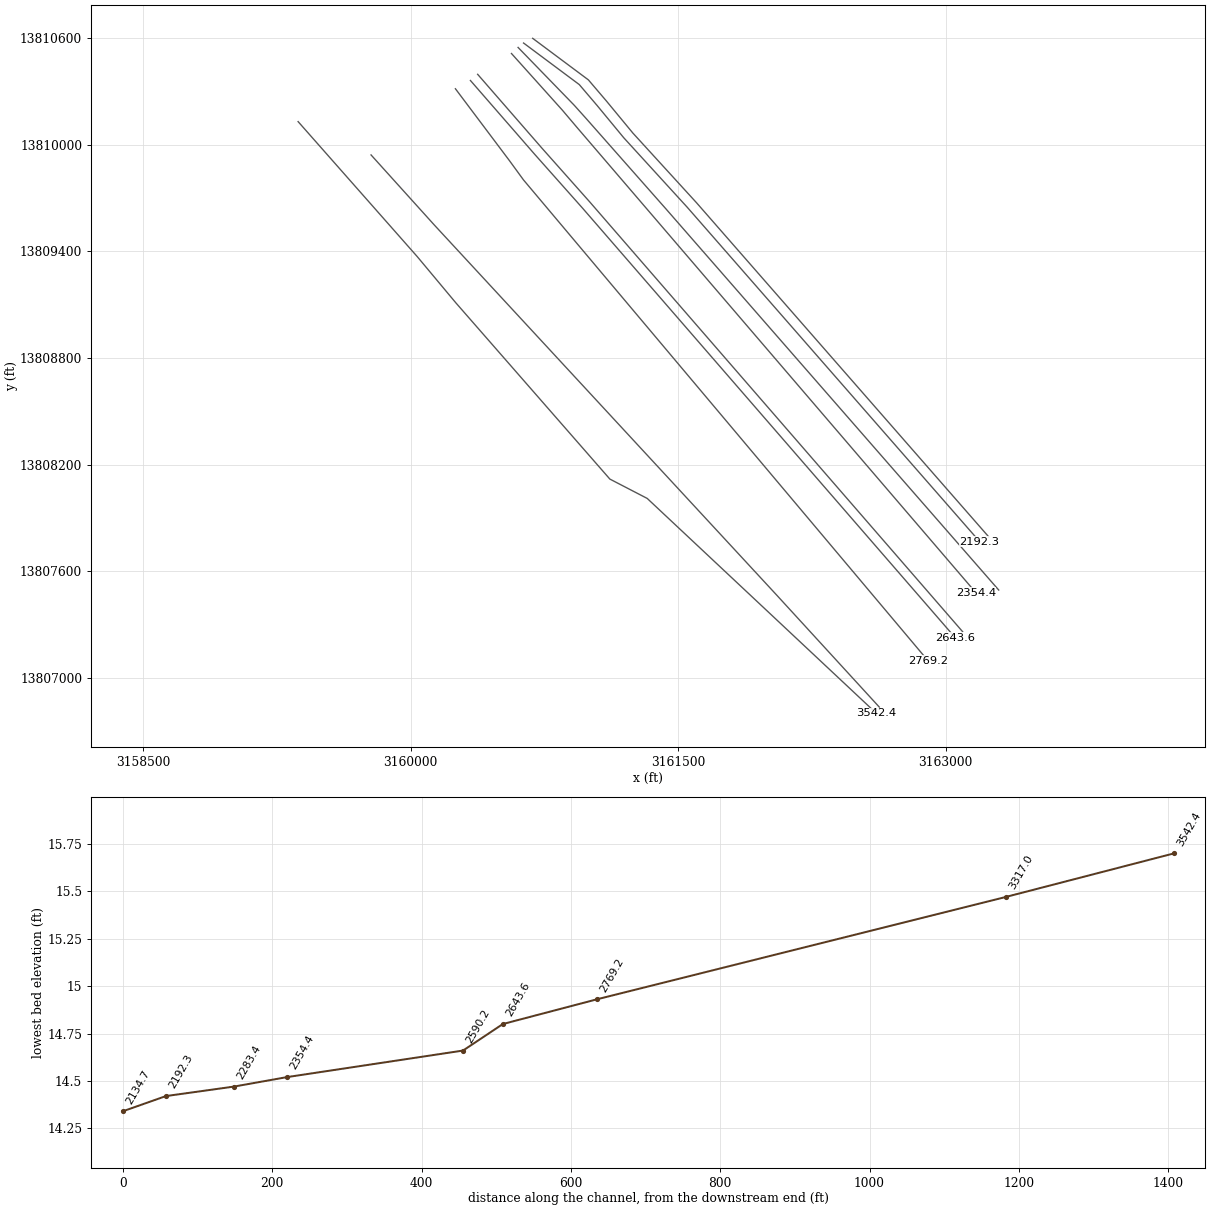
HEC-RAS study C106-03-00.PRJ: C106-03-00

--- C106-03-00.g01 (geometry) --- (continued)

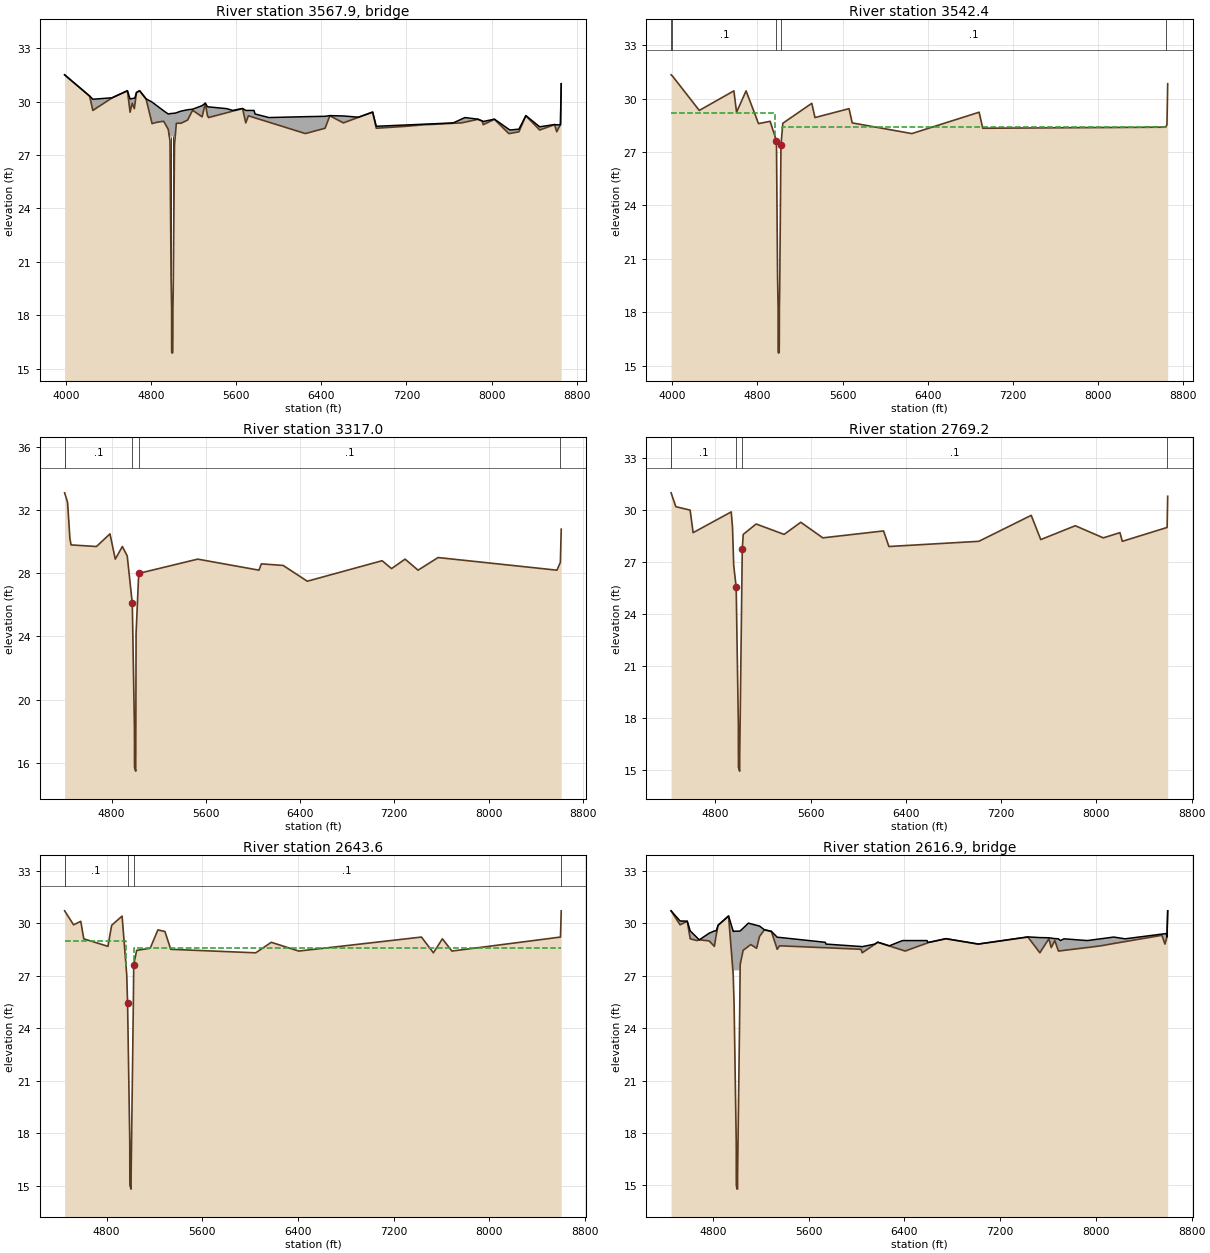
Type RM Length L Ch R = 3 ,3567.9  ,,,
BEGIN DESCRIPTION:
MAIN STREET
Structure ID: C63-8
END DESCRIPTION:
Bridge Culvert--1,0,-1,-1, 0
Deck Dist Width WeirC Skew NumUp NumDn MinLoCord MaxHiCord MaxSubmerge Is_Ogee
10,31,2.6,0, 56, 56, , , 0.95, 0, 1,1,,
  3988.8  4223.8  4253.8  4433.8  4578.8  4603.8  4623.8  4643.8  4648.7  4663.8
  4693.3  4754.1  4810.1  4919.1  4962.2  4972.5  4978.7 5027.99  5038.4  5081.4
  5144.6  5191.3  5280.6  5310.5  5330.5  5340.5  5512.9  5567.9  5660.5  5690.5
  5715.5  5767.9  5777.9  5907.9  6250.5  6435.5  6480.5  6607.4  6748.1  6882.4
  6916.5  7639.4  7749.4  7871.5  7911.5  7921.5  8026.5  8161.5  8174.4  8256.5
  8321.5  8451.5  8591.5  8611.5  8646.8  8653.8
    31.5   30.31   30.13   30.21   30.61   30.14   30.17   30.19    30.2   30.51
   30.61   30.15   29.97   29.48    29.3   29.31   29.32   29.35   29.37   29.46
   29.54   29.57   29.77   29.91   29.71    29.7    29.6    29.5   29.61    29.5
    29.5    29.5    29.3    29.1   29.15   29.17   29.21   29.19   29.12   29.41
   28.61    28.8    29.1   29.01   28.91   28.88   29.01   28.44    28.4   28.45
   29.21   28.58   28.71   28.69    28.7      31
    31.5    30.3    29.5    30.2    30.6    29.4    29.9    29.6   29.82    30.5
    30.6   30.14   28.76   28.89   28.44   28.03   28.02   28.05   28.78   28.78
   28.96   29.51   29.14    29.9    29.2    29.1   29.37   29.46    29.6    28.8
    29.2    29.1   29.08   28.84    28.2    28.5    29.2    28.8   29.11    29.4
    28.5   28.78   28.84      29    28.9    28.7      29    28.2   28.21    28.3
    29.2    28.4    28.7    28.3    28.7      31
  3988.8  4223.8  4253.8  4433.8  4578.8  4603.8  4623.8  4643.8  4648.7  4663.8
  4693.3  4754.1  4810.1  4919.1  4962.2  4972.5  4978.7 5027.99  5038.4  5081.4
  5144.6  5191.3  5280.6  5310.5  5330.5  5340.5  5512.9  5567.9  5660.5  5690.5
  5715.5  5767.9  5777.9  5907.9  6250.5  6435.5  6480.5  6607.4  6748.1  6882.4
  6916.5  7639.4  7749.4  7871.5  7911.5  7921.5  8026.5  8161.5  8174.4  8256.5
  8321.5  8451.5  8591.5  8611.5  8646.8  8653.8
    31.5   30.31   30.13   30.21   30.61   30.14   30.17   30.19    30.2   30.51
   30.61   30.15   29.97   29.48    29.3   29.31   29.32   29.35   29.37   29.46
   29.54   29.57   29.77   29.91   29.71    29.7    29.6    29.5   29.61    29.5
    29.5    29.5    29.3    29.1   29.15   29.17   29.21   29.19   29.12   29.41
   28.61    28.8    29.1   29.01   28.91   28.88   29.01   28.44    28.4   28.45
   29.21   28.58   28.71   28.69    28.7      31
   31.34   30.14   29.34   30.04   30.44   29.24   29.74   29.44   29.66   30.34
   30.44   29.98    28.6   28.73   28.28   27.87   27.86   27.89   28.62   28.62
    28.8   29.35   28.98   29.74   29.04   28.94   29.21    29.3   29.44   28.64
   29.04   28.94   28.92   28.68   28.04   28.34   29.04   28.64   28.95   29.24
   28.34   28.62   28.68   28.84   28.74   28.54   28.84   28.04   28.05   28.14
   29.04   28.24   28.54   28.14   28.54   30.84
Pier Skew, UpSta & Num, DnSta & Num=  ,4988.9, 2 ,4988.9, 2 , 0 , 0 , 0 ,,
     1.6     1.6
   18.91   29.02
     1.6     1.6
   18.75   28.86
Pier Skew, UpSta & Num, DnSta & Num=  ,5009, 2 ,5009, 2 , 0 , 0 , 0 ,,
     1.6     1.6
   18.12   29.04
     1.6     1.6
   17.96   28.88
Abutment Skew #Up #Dn= , 2 , 2
  4972.3  4994.1
   28.03    18.4
  4972.3  4994.1
   27.87   18.24
Abutment Skew #Up #Dn= , 2 , 2
  5006.1 5028.79
   18.39   28.09
  5006.1 5028.79
   18.23   27.93
BR Coef= 1 , 1 , 0 ,1.25, 0 ,,,0.8,-1,2,0,
WSPro=,,,, 1 ,,,, 0 ,,,, 0 ,,,,-1 ,-1 ,-1 , 0 , 0 , 0 , 0 , 0
BR U #Sta/Elev= 103
  3988.8    31.5    4002   31.43    4142   30.72    4152   30.67  4223.8    30.3
  4253.8    29.5  4433.8    30.2    4462   30.28    4502   30.39  4578.8    30.6
  4603.8    29.4  4623.8    29.9  4643.8    29.6  4648.7   29.82  4663.8    30.5
  4693.3    30.6  4752.5   30.15  4754.1   30.14  4805.8   28.87  4810.1   28.76
  4851.9   28.83  4902.8   28.88  4919.1   28.89  4962.2   28.44  4968.5   28.19
  4968.7   28.18 4969.19   28.16  4969.3   28.16 4969.41   28.16 4972.41   28.04
  4972.5   28.03  4978.7   27.79  4988.9   20.19    4994   18.43  4994.1    18.4
  4994.2   16.77  4994.5   15.92  4998.8   15.87  5004.6   15.91  5005.7   16.89
    5006   18.02  5006.1   18.39    5009    19.4  5020.9   27.55 5027.99   28.05
  5028.1   28.06 5028.21   28.06 5028.59   28.09  5028.7    28.1  5028.8   28.11
  5028.9   28.11  5038.4   28.78  5081.4   28.78  5100.3   28.83  5144.6   28.96
  5191.3   29.51  5200.5   29.47  5280.6   29.14  5284.5   29.24  5310.5    29.9
  5330.5    29.2  5337.9   29.13  5340.5    29.1  5512.9   29.37  5567.9   29.46
  5660.5    29.6  5690.5    28.8  5715.5    29.2  5767.9    29.1  5777.9   29.08
  5907.9   28.84  6250.5    28.2  6435.5    28.5  6480.5    29.2  6607.4    28.8
  6653.1    28.9  6748.1   29.11  6873.1   29.38  6882.4    29.4  6916.5    28.5
  7176.5    28.6  7376.5    28.7  7454.4   28.72  7529.4   28.74  7639.4   28.78
  7716.5    28.8  7749.4   28.84  7871.5      29  7879.4   28.98  7911.5    28.9
  7921.5    28.7  8026.5      29  8049.4   28.86  8161.5    28.2  8174.4   28.21
  8256.5    28.3  8321.5    29.2  8451.5    28.4  8591.5    28.7  8611.5    28.3
  8634.2   28.56  8646.8    28.7  8653.8      31
BR U #Mann= 5
  3988.8      .2    4002      .1  4978.7    .015  5020.9      .1  8634.2      .2
BR U Banks=4978.7,5020.9
BR D #Sta/Elev= 103
  3988.8   31.34    4002   31.27    4142   30.56    4152   30.51  4223.8   30.14
  4253.8   29.34  4433.8   30.04    4462   30.12    4502   30.23  4578.8   30.44
  4603.8   29.24  4623.8   29.74  4643.8   29.44  4648.7   29.66  4663.8   30.34
  4693.3   30.44  4752.5   29.99  4754.1   29.98  4805.8   28.71  4810.1    28.6
  4851.9   28.67  4902.8   28.72  4919.1   28.73  4962.2   28.28  4968.5   28.03
  4968.7   28.02 4969.19      28  4969.3      28 4969.41      28 4972.41   27.88
  4972.5   27.87  4978.7   27.63  4988.9   20.03    4994   18.27  4994.1   18.24
  4994.2   16.61  4994.5   15.76  4998.8   15.71  5004.6   15.75  5005.7   16.73
    5006   17.86  5006.1   18.23    5009   19.24  5020.9   27.39 5027.99   27.89
  5028.1    27.9 5028.21    27.9 5028.59   27.93  5028.7   27.94  5028.8   27.95
  5028.9   27.95  5038.4   28.62  5081.4   28.62  5100.3   28.67  5144.6    28.8
  5191.3   29.35  5200.5   29.31  5280.6   28.98  5284.5   29.08  5310.5   29.74
  5330.5   29.04  5337.9   28.97  5340.5   28.94  5512.9   29.21  5567.9    29.3
  5660.5   29.44  5690.5   28.64  5715.5   29.04  5767.9   28.94  5777.9   28.92
  5907.9   28.68  6250.5   28.04  6435.5   28.34  6480.5   29.04  6607.4   28.64
  6653.1   28.74  6748.1   28.95  6873.1   29.22  6882.4   29.24  6916.5   28.34
  7176.5   28.44  7376.5   28.54  7454.4   28.56  7529.4   28.58  7639.4   28.62
  7716.5   28.64  7749.4   28.68  7871.5   28.84  7879.4   28.82  7911.5   28.74
  7921.5   28.54  8026.5   28.84  8049.4    28.7  8161.5   28.04  8174.4   28.05
  8256.5   28.14  8321.5   29.04  8451.5   28.24  8591.5   28.54  8611.5   28.14
  8634.2    28.4  8646.8   28.54  8653.8   30.84
BR D #Mann= 5
  3988.8      .2    4002      .1  4978.7    .015  5020.9      .1  8634.2      .2
BR D Banks=4978.7,5020.9
BC Design=,, 0 ,, 0 ,,,,,,
BC HTab HWMax=31.52
BC Use User HTab Curves=0
BC User HTab FreeFlow(D)= 0

Type RM Length L Ch R = 1 ,3542.4  ,225.4,225.4,225.4
BEGIN DESCRIPTION:
Downstream Section of Bridge/Culvert/Weir
END DESCRIPTION:
XS GIS Cut Line= 6
      3159367.92     13810128.72      3160036.14     13809369.83
      3160252.45     13809110.26      3161116.81     13808119.02
      3161326.49     13808010.14      3162612.19      13806801.7
#Sta/Elev= 30
  3988.8   31.33    4002   31.26  4253.8   29.33  4578.8   30.43  4603.8   29.23
  4693.3   30.43  4810.1   28.59  4919.1   28.72  4978.7   27.62  4988.9   20.02
  4994.1   18.23  4994.2    16.6  4994.5   15.75  4998.8    15.7  5004.6   15.74
  5005.7   16.72  5006.1   18.22    5009   19.23  5020.9   27.38  5038.4   28.61
  5310.5   29.73  5340.5   28.93  5660.5   29.43  5690.5   28.63  6250.5   28.03
  6882.4   29.23  6916.5   28.33  8634.2   28.39  8646.8   28.53  8653.8   30.83
#Mann= 5 , 1 , 0
  3988.8      .2       0    4002      .1       0  4978.7    .015       0
  5020.9      .1       0  8634.2      .2       0
#XS Ineff= 2 , 0
       0    4963    29.2    5034       0    28.4
Permanent Ineff=
       F       F
Bank Sta=4978.7,5020.9
XS Rating Curve= 0 ,0
Exp/Cntr=0.5,0.3

Type RM Length L Ch R = 1 ,3317.0  ,547.7,547.8,754.3
BEGIN DESCRIPTION:
Cross Section 3317.0-Interpolated
END DESCRIPTION:
XS GIS Cut Line= 5
      3159777.09     13809941.45      3160132.83     13809546.54
      3160250.33     13809419.25      3162053.83     13807465.59
      3162628.33     13806837.23
#Sta/Elev= 30
  4401.5    33.1  4426.5    32.5  4446.5    30.2  4456.5    29.8  4671.5    29.7
  4786.5    30.5  4831.5    28.9  4891.5    29.7    4933    29.1  4975.9    26.1
  4994.2   18.16  4994.7   16.08  4995.1   15.69  5005.1   15.47    5008    24.2
    5028    27.6    5033      28  5531.2    28.9  6051.2    28.2  6071.2    28.6
  6256.2    28.5  6461.2    27.5  7096.2    28.8  7176.2    28.3  7291.2    28.9
  7401.2    28.2  7571.2      29  8580.1    28.2  8609.2    28.7  8616.5    30.8
#Mann= 5 , 1 , 0
  4401.5      .2       0  4401.5      .1       0  4975.9    .015       0
    5033      .1       0  8609.2      .2       0
Bank Sta=4975.9,5033
XS Rating Curve= 0 ,0
Exp/Cntr=0.3,0.1

Type RM Length L Ch R = 1 ,2769.2  ,116.3,125.6,127.9
BEGIN DESCRIPTION:
Cross Section 2769.2-Interpolated
END DESCRIPTION:
XS GIS Cut Line= 4
      3160250.33     13810313.51      3160553.85     13809908.81
      3160632.18     13809801.11      3162902.58     13807096.81
#Sta/Elev= 30
  4429.3      31  4469.3    30.2  4589.3      30  4614.3    28.7  4934.3    29.9
  4945.2      29  4955.2    26.8  4975.9   25.56  4994.2   17.62  4994.7   15.54
  4995.1   15.15  5005.1   14.93  5005.4   15.71  5027.1   27.77  5035.2    28.6
  5143.4    29.2  5378.4    28.6  5518.4    29.3  5703.4    28.4  6213.4    28.8
  6258.4    27.9  7013.4    28.2  7453.4    29.7  7533.4    28.3  7823.4    29.1
  8058.4    28.4  8198.4    28.7  8218.4    28.2  8594.3      29  8599.3    30.8
#Mann= 5 , 1 , 0
  4429.3      .2       0  4429.3      .1       0  4975.9    .015       0
  5027.1      .1       0  8594.3      .2       0
Bank Sta=4975.9,5027.1
XS Rating Curve= 0 ,0
Exp/Cntr=0.5,0.3

Type RM Length L Ch R = 1 ,2643.6  ,53.4,53.4,53.4
BEGIN DESCRIPTION:
Upstream Section of Bridge/Culvert/Weir
END DESCRIPTION:
XS GIS Cut Line= 4
      3160334.55       13810360.      3160696.17     13809943.72
      3160963.23     13809642.69       3163055.3     13807226.35
#Sta/Elev= 30
  4449.7   30.71  4524.7   29.91  4584.7   30.11  4609.7   29.11  4811.6   28.68
  4842.6   29.88    4930   30.41  4968.8   27.06  4975.9   25.43  4994.2   17.49
  4994.7   15.41  4995.1   15.02  5005.1    14.8  5005.4   15.58  5023.7   25.25
  5027.1   27.64    5052   28.45  5164.6   28.57  5229.2   29.62  5287.9   29.53
  5336.6   28.51  6046.6   28.31  6176.6   28.91  6406.6   28.41  7431.6   29.21
  7531.6   28.31  7606.6   29.11  7686.6   28.41  8593.6   29.21  8599.7   30.71
#Mann= 5 , 1 , 0
  4449.7      .2       0  4449.7      .1       0  4975.9    .015       0
  5027.1      .1       0  8593.6      .2       0
#XS Ineff= 2 , 0
       0    4965      29    5033       0    28.6
Permanent Ineff=
       F       F
Bank Sta=4975.9,5027.1
XS Rating Curve= 0 ,0
Exp/Cntr=0.5,0.3

Type RM Length L Ch R = 3 ,2616.9  ,,,
BEGIN DESCRIPTION:
STATE ROAD
Structure ID: C63-7
END DESCRIPTION:
Bridge Culvert--1,0,-1,-1, 0
Deck Dist Width WeirC Skew NumUp NumDn MinLoCord MaxHiCord MaxSubmerge Is_Ogee
10,33.4,2.6,0, 56, 56, , , 0.95, 0, 1,1,,
  4449.7  4524.7  4584.7  4609.7  4664.7  4685.1  4767.6  4811.6  4826.8  4842.6
    4930  4968.8 4975.11  4975.2 5023.29  5023.4  5027.1    5052  5096.2  5115.4
  5164.6  5188.4  5229.2  5287.9  5336.6  5356.6  5738.5  5743.5  6036.6  6046.6
  6153.5  6176.6  6273.5  6383.5  6406.6  6588.5  6593.5  6606.6  6746.6  7016.6
  7431.6  7531.6  7606.6  7626.6  7656.6  7686.6  7703.5  7733.5  7928.5  8148.5
  8243.5  8551.6  8576.6  8588.7  8593.6  8599.7
    30.7   30.12   30.11   29.55   29.18   29.04   29.42   29.55   29.56   29.88
   30.41   29.53   29.53   29.53   29.54   29.54   29.55   29.71      30   29.96
   29.87   29.83   29.62   29.53   29.19   29.18    28.9    28.8   28.66   28.65
    28.8   28.91    28.7      29      29      29    28.9    28.9   29.11    28.8
   29.21   29.17   29.16   29.14   29.11    29.1      29    29.1      29    29.2
    29.1   29.37   29.39    29.4    29.2    30.7
    30.7    29.9    30.1    29.1      29   29.04   28.98   28.67   29.31   29.87
    30.4   27.05    25.6   27.29    27.3   25.08   27.63   28.44   28.67   28.77
   28.56   29.23   29.61   29.52    28.5    28.7   28.59   28.59    28.5    28.3
   28.79    28.9   28.69   28.45    28.4   28.85   28.87    28.9    29.1    28.8
    29.2    28.3    29.1    28.6      29    28.4   28.41   28.44    28.6   28.83
   28.94    29.3    28.8   29.08    29.2    30.7
  4449.7  4524.7  4584.7  4609.7  4664.7  4685.1  4767.6  4811.6  4826.8  4842.6
    4930  4968.8 4975.11  4975.2 5023.29  5023.4  5027.1    5052  5096.2  5115.4
  5164.6  5188.4  5229.2  5287.9  5336.6  5356.6  5738.5  5743.5  6036.6  6046.6
  6153.5  6176.6  6273.5  6383.5  6406.6  6588.5  6593.5  6606.6  6746.6  7016.6
  7431.6  7531.6  7606.6  7626.6  7656.6  7686.6  7703.5  7733.5  7928.5  8148.5
  8243.5  8551.6  8576.6  8588.7  8593.6  8599.7
    30.7   30.12   30.11   29.55   29.18   29.04   29.42   29.55   29.56   29.88
   30.41   29.53   29.53   29.53   29.54   29.54   29.55   29.71      30   29.96
   29.87   29.83   29.62   29.53   29.19   29.18    28.9    28.8   28.66   28.65
    28.8   28.91    28.7      29      29      29    28.9    28.9   29.11    28.8
   29.21   29.17   29.16   29.14   29.11    29.1      29    29.1      29    29.2
    29.1   29.37   29.39    29.4    29.2    30.7
   30.58   29.78   29.98   28.98   28.88   28.92   28.86   28.55   29.19   29.75
   30.28   26.93   25.48   27.17   27.18   24.96   27.51   28.32   28.55   28.65
   28.44   29.11   29.49    29.4   28.38   28.58   28.47   28.47   28.38   28.18
   28.67   28.78   28.57   28.33   28.28   28.73   28.75   28.78   28.98   28.68
   29.08   28.18   28.98   28.48   28.88   28.28   28.29   28.32   28.48   28.71
   28.82   29.18   28.68   28.96   29.08   30.58
Abutment Skew #Up #Dn= , 2 , 2
    4975  4976.3
   27.29   25.32
    4975  4976.3
   27.17    25.2
Abutment Skew #Up #Dn= , 2 , 2
  5022.2 5023.49
   24.45    27.3
  5022.2 5023.49
   24.33   27.18
BR Coef= 1 , 1 , 0 ,1.25, 0 ,,,0.8,0,2,0,
WSPro=,,,, 1 ,,,, 0 ,,,, 0 ,,,,-1 ,-1 ,-1 , 0 , 0 , 0 , 0 , 0
BR U #Sta/Elev= 95
  4449.7    30.7  4497.3   30.19  4524.7    29.9  4584.7    30.1  4609.7    29.1
  4664.7      29  4685.1   29.04  4686.6   29.04  4767.6   28.98  4790.2   28.82
  4811.6   28.67  4826.8   29.31  4842.6   29.87  4897.6    30.2    4930    30.4
  4968.8   27.05 4968.89   27.03    4969      27 4969.11   26.98    4975   25.63
 4975.11    25.6  4975.2   25.58  4975.9   25.42  4976.2   25.35  4976.3   25.32
  4994.2   17.48  4994.7    15.4  4995.1   15.01  5000.2    14.8  5005.1   14.79
  5005.4   15.57  5022.2   24.45 5023.29   25.02  5023.4   25.08  5023.7   25.24
  5025.3   26.36  5025.4   26.43  5027.1   27.63 5030.79   27.75    5031   27.76
 5031.11   27.76    5052   28.44  5096.2   28.67  5115.4   28.77  5164.6   28.56
  5187.7   29.21  5188.4   29.23  5229.2   29.61    5285   29.52  5287.9   29.52
  5336.6    28.5  5356.6    28.7  5738.5   28.59  5743.5   28.59  6036.6    28.5
  6046.6    28.3  6153.5   28.79  6158.5   28.82  6176.6    28.9  6268.5    28.7
  6273.5   28.69  6383.5   28.45  6406.6    28.4  6493.5   28.62  6588.5   28.85
  6593.5   28.87  6606.6    28.9  6648.5   28.96  6746.6    29.1  6918.5   28.91
  6978.5   28.84  7016.6    28.8  7068.5   28.85  7431.6    29.2  7531.6    28.3
  7573.5   28.75  7606.6    29.1  7626.6    28.6  7656.6      29  7663.5   28.86
  7686.6    28.4  7693.5   28.41  7703.5   28.41  7733.5   28.44  7928.5    28.6
  8041.6    28.7  8083.5   28.75  8148.5   28.83  8243.5   28.94  8328.5   29.04
  8551.6    29.3  8576.6    28.8  8588.7   29.08  8593.6    29.2  8599.7    30.7
BR U #Mann= 5
  4449.7      .2  4449.7      .1  4975.9    .015  5027.1      .1  8593.6      .2
BR U Banks=4975.9,5027.1
BR D #Sta/Elev= 95
  4449.7   30.58  4497.3   30.07  4524.7   29.78  4584.7   29.98  4609.7   28.98
  4664.7   28.88  4685.1   28.92  4686.6   28.92  4767.6   28.86  4790.2    28.7
  4811.6   28.55  4826.8   29.19  4842.6   29.75  4897.6   30.08    4930   30.28
  4968.8   26.93 4968.89   26.91    4969   26.88 4969.11   26.86    4975   25.51
 4975.11   25.48  4975.2   25.46  4975.9    25.3  4976.2   25.23  4976.3    25.2
  4994.2   17.36  4994.7   15.28  4995.1   14.89  5000.2   14.68  5005.1   14.67
  5005.4   15.45  5022.2   24.33 5023.29    24.9  5023.4   24.96  5023.7   25.12
  5025.3   26.24  5025.4   26.31  5027.1   27.51 5030.79   27.63    5031   27.64
 5031.11   27.64    5052   28.32  5096.2   28.55  5115.4   28.65  5164.6   28.44
  5187.7   29.09  5188.4   29.11  5229.2   29.49    5285    29.4  5287.9    29.4
  5336.6   28.38  5356.6   28.58  5738.5   28.47  5743.5   28.47  6036.6   28.38
  6046.6   28.18  6153.5   28.67  6158.5    28.7  6176.6   28.78  6268.5   28.58
  6273.5   28.57  6383.5   28.33  6406.6   28.28  6493.5    28.5  6588.5   28.73
  6593.5   28.75  6606.6   28.78  6648.5   28.84  6746.6   28.98  6918.5   28.79
  6978.5   28.72  7016.6   28.68  7068.5   28.73  7431.6   29.08  7531.6   28.18
  7573.5   28.63  7606.6   28.98  7626.6   28.48  7656.6   28.88  7663.5   28.74
  7686.6   28.28  7693.5   28.29  7703.5   28.29  7733.5   28.32  7928.5   28.48
  8041.6   28.58  8083.5   28.63  8148.5   28.71  8243.5   28.82  8328.5   28.92
  8551.6   29.18  8576.6   28.68  8588.7   28.96  8593.6   29.08  8599.7   30.58
BR D #Mann= 5
  4449.7      .2  4449.7      .1  4975.9    .015  5027.1      .1  8593.6      .2
BR D Banks=4975.9,5027.1
BC Design=,, 0 ,, 0 ,,,,,,
BC HTab HWMax=30.71
BC Use User HTab Curves=0
BC User HTab FreeFlow(D)= 0

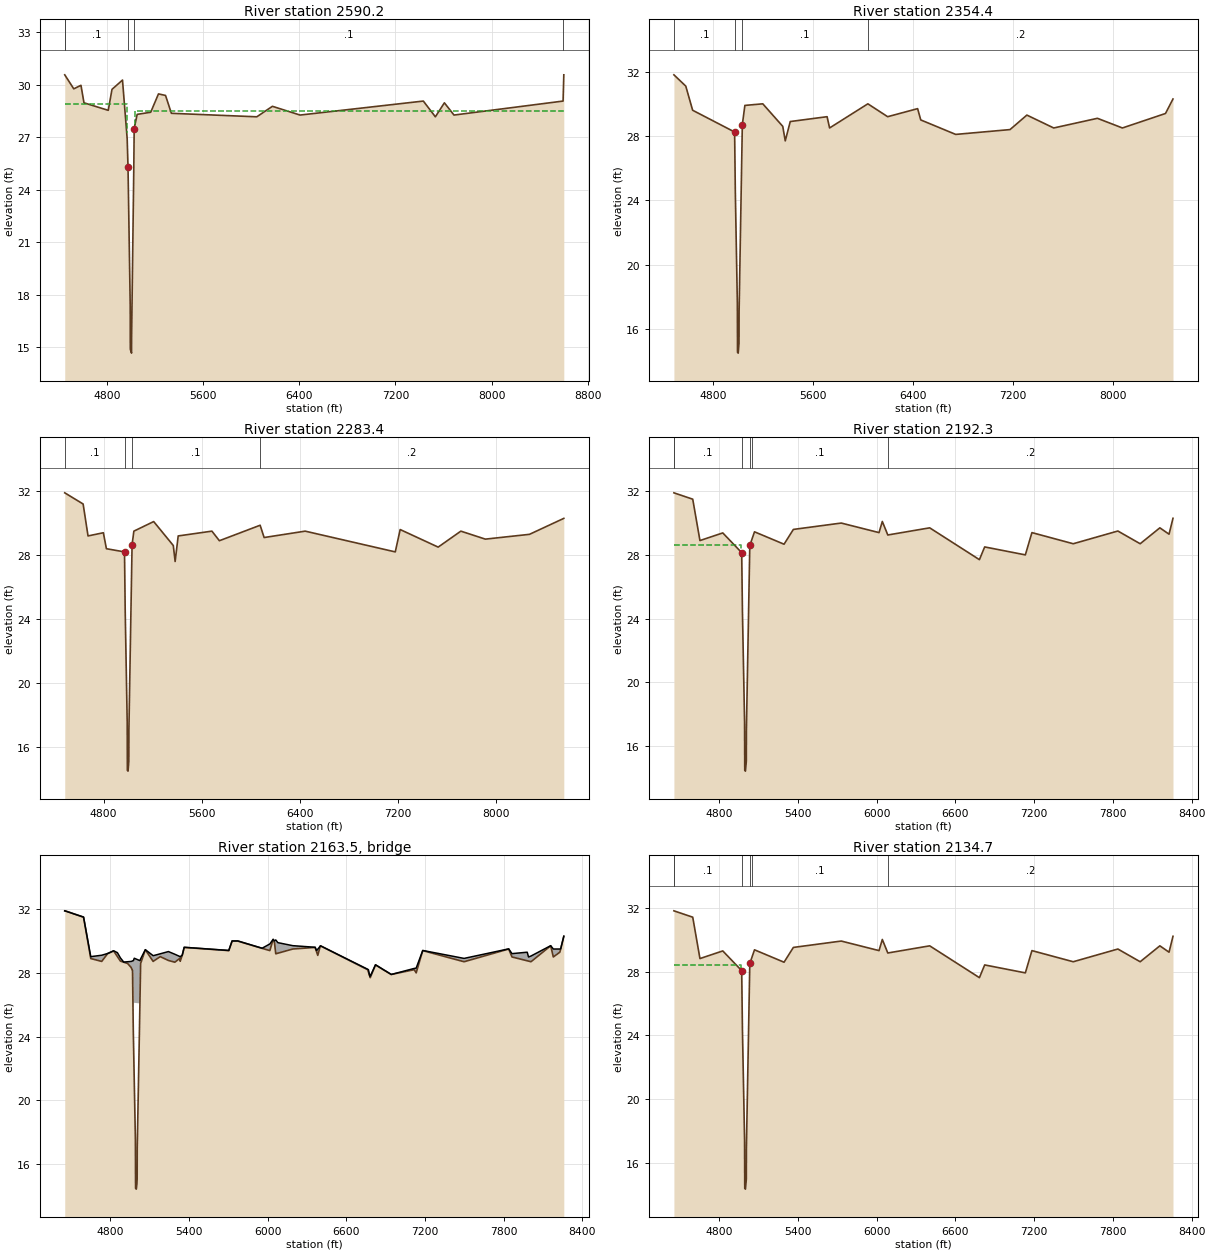
Type RM Length L Ch R = 1 ,2590.2  ,235.8,235.8,235.8
BEGIN DESCRIPTION:
Downstream Section of Bridge/Culvert/Weir
END DESCRIPTION:
XS GIS Cut Line= 4
      3160375.17     13810394.66      3160736.79     13809978.38
      3161003.85     13809677.35      3163095.93     13807261.01
#Sta/Elev= 30
  4449.7   30.57  4524.7   29.77  4584.7   29.97  4609.7   28.97  4811.6   28.54
  4842.6   29.74    4930   30.27  4968.8   26.92  4975.9   25.29  4994.2   17.35
  4994.7   15.27  4995.1   14.88  5005.1   14.66  5005.4   15.44  5023.7   25.11
  5027.1    27.5    5052   28.31  5164.6   28.43  5229.2   29.48  5287.9   29.39
  5336.6   28.37  6046.6   28.17  6176.6   28.77  6406.6   28.27  7431.6   29.07
  7531.6   28.17  7606.6   28.97  7686.6   28.27  8593.6   29.07  8599.7   30.57
#Mann= 5 , 1 , 0
  4449.7      .2       0  4449.7      .1       0  4975.9    .015       0
  5027.1      .1       0  8593.6      .2       0
#XS Ineff= 2 , 0
       0    4965    28.9    5033       0    28.5
Permanent Ineff=
       F       F
Bank Sta=4975.9,5027.1
XS Rating Curve= 0 ,0
Exp/Cntr=0.5,0.3

Type RM Length L Ch R = 1 ,2354.4  ,71,71,72.2
BEGIN DESCRIPTION:
Cross Section 2354.4-Interpolated
END DESCRIPTION:
XS GIS Cut Line= 4
      3160564.87     13810511.67      3160849.55     13810194.06
      3160935.71     13810092.23      3163169.94     13807480.76
#Sta/Elev= 30
    4485    31.8    4580    31.1    4635    29.6  4971.1   28.25  4976.8   24.55
    4993   17.63  4994.4   14.57  4999.8   14.52  5006.4   15.14    5007    17.1
  5032.9    28.7  5053.3    29.9  5196.7      30  5356.7    28.6  5376.7    27.7
  5416.7    28.9  5711.7    29.2  5731.7    28.5  6038.2      30  6196.7    29.2
  6436.7    29.7  6461.7      29  6741.7    28.1  7176.7    28.4  7311.7    29.3
  7526.7    28.5  7876.7    29.1  8076.7    28.5  8421.7    29.4  8481.7    30.3
#Mann= 4 , 1 , 0
    4485      .1       0  4971.1    .015       0  5032.9      .1       0
  6038.2      .2       0
Bank Sta=4971.1,5032.9
XS Rating Curve= 0 ,0
Exp/Cntr=0.3,0.1

Type RM Length L Ch R = 1 ,2283.4  ,89.1,91.1,95.2
BEGIN DESCRIPTION:
Cross Section 2283.4-Interpolated
END DESCRIPTION:
XS GIS Cut Line= 5
      3160602.03     13810545.67      3160917.43     13810220.17
      3160985.32     13810144.45      3161432.25     13809637.16
      3163298.42      13807495.2
#Sta/Elev= 30
  4483.5    31.9  4633.5    31.2  4673.5    29.2  4798.5    29.4  4823.5    28.4
  4971.1    28.2  4976.8    24.5    4993   17.58  4994.4   14.52  4999.8   14.47
  5006.4   15.09    5007   17.05  5032.9   28.65  5047.5    29.5  5209.2    30.1
  5369.2    28.6  5384.2    27.6  5409.2    29.2  5684.2    29.5  5745.3    28.9
  6077.7   29.87  6110.3    29.1  6445.3    29.5  7180.3    28.2  7220.3    29.6
  7530.3    28.5  7715.3    29.5  7915.3      29  8275.3    29.3  8555.4    30.3
#Mann= 4 , 1 , 0
  4483.5      .1       0  4971.1    .015       0  5032.9      .1       0
  6077.7      .2       0
Bank Sta=4971.1,5032.9
XS Rating Curve= 0 ,0
Exp/Cntr=0.5,0.3

Type RM Length L Ch R = 1 ,2192.3  ,57.6,57.6,57.6
BEGIN DESCRIPTION:
Upstream Section of Bridge/Culvert/Weir
END DESCRIPTION:
XS GIS Cut Line= 6
      3160632.68     13810570.61      3160945.28     13810336.93
      3161045.57     13810219.07      3161194.43     13810038.39
      3161551.51     13809646.61      3163191.33     13807767.66
#Sta/Elev= 30
  4454.6   31.91    4598   31.51    4653   28.91    4827   29.39  4971.1   28.15
  4976.8   24.45    4993   17.53  4994.4   14.47  4999.8   14.42  5006.4   15.04
    5007      17  5032.9    28.6  5068.8   29.46  5293.9   28.68  5364.9   29.61
  5729.9   30.01  6017.7   29.41  6042.7   30.11  6084.6   29.26  6403.8   29.71
  6782.7   27.71  6822.7   28.51  7132.7   28.01  7182.7   29.41  7497.7   28.71
  7837.7   29.51  8007.7   28.71  8157.7   29.71  8227.7   29.31  8257.7   30.31
#Mann= 6 , 1 , 0
  4454.6      .2       0  4454.6      .1       0  4971.1    .015       0
  5032.9      .1       0  5049.6      .1       0  6084.6      .2       0
#XS Ineff= 2 , 0
       0  4967.6    28.6  5037.2       0    28.7
Permanent Ineff=
       F       F
Bank Sta=4971.1,5032.9
XS Rating Curve= 0 ,0
Exp/Cntr=0.5,0.3

Type RM Length L Ch R = 3 ,2163.5  ,,,
BEGIN DESCRIPTION:
DALLAS STREET
Structure ID: C63-6
END DESCRIPTION:
Bridge Culvert--1,0,-1,-1, 0
Deck Dist Width WeirC Skew NumUp NumDn MinLoCord MaxHiCord MaxSubmerge Is_Ogee
10,37.6,2.6,0, 60, 60, , , 0.95, 0, 1,1,,
  4454.6    4598    4653  4736.4  4781.6    4827    4856    4879    4904  4960.6
  4971.1  4976.8 4977.81  4977.9  4984.4 5027.49  5032.9  5068.8  5128.3  5182.6
  5244.6  5293.9    5334  5334.3  5349.9  5364.9  5704.9  5729.9  5772.7  5958.8
  6017.7  6042.7  6052.7  6062.7  6078.8  6192.7  6362.7  6373.8  6382.7  6403.8
  6762.7  6768.8  6778.8  6782.7  6822.7  6942.7  7117.7  7132.7  7182.7  7497.7
  7837.7  7862.7  7978.8  7988.8  8007.7  8157.7  8177.7  8227.7  8233.8  8257.7
    31.9   31.51   29.02   29.11   29.22   29.39   29.27   28.94   28.68   28.72
   28.75   28.77   28.77   28.77   28.92   28.77   28.88   29.46   29.08    29.2
   29.34   29.17   29.02   29.02   29.11   29.61   29.41   30.01   30.01   29.55
   29.82   30.11   30.01   30.07    29.9   29.71   29.61    29.4   29.49    29.7
   28.23    28.2    27.8   27.79   28.51    27.9   28.28    28.3   29.41   28.91
   29.51   29.21    29.3      29   29.06   29.71    29.5    29.5   29.51    30.3
    31.9    31.5    28.9   28.72   29.21   29.38   29.02   28.74   28.67   28.34
   28.14   24.44   24.01   25.97   26.12   26.08   28.59   29.45   28.72   29.02
   28.78   28.67   28.93   28.73    29.1    29.6    29.4      30      30   29.54
    29.4    30.1    29.9    29.2   29.24    29.5    29.6   29.32    29.1    29.7
    28.2   28.05    27.8    27.7    28.5    27.9    28.2      28    29.4    28.7
    29.5      29   28.76   28.74    28.7    29.7      29    29.3    29.5    30.3
  4454.6    4598    4653  4736.4  4781.6    4827    4856    4879    4904  4960.6
  4971.1  4976.8 4977.81  4977.9  4984.4 5027.49  5032.9  5068.8  5128.3  5182.6
  5244.6  5293.9    5334  5334.3  5349.9  5364.9  5704.9  5729.9  5772.7  5958.8
  6017.7  6042.7  6052.7  6062.7  6078.8  6192.7  6362.7  6373.8  6382.7  6403.8
  6762.7  6768.8  6778.8  6782.7  6822.7  6942.7  7117.7  7132.7  7182.7  7497.7
  7837.7  7862.7  7978.8  7988.8  8007.7  8157.7  8177.7  8227.7  8233.8  8257.7
    31.9   31.51   29.02   29.11   29.22   29.39   29.27   28.94   28.68   28.72
   28.75   28.77   28.77   28.77   28.92   28.77   28.88   29.46   29.08    29.2
   29.34   29.17   29.02   29.02   29.11   29.61   29.41   30.01   30.01   29.55
   29.82   30.11   30.01   30.07    29.9   29.71   29.61    29.4   29.49    29.7
   28.23    28.2    27.8   27.79   28.51    27.9   28.28    28.3   29.41   28.91
   29.51   29.21    29.3      29   29.06   29.71    29.5    29.5   29.51    30.3
   31.83   31.43   28.83   28.65   29.14   29.31   28.95   28.67    28.6   28.27
   28.07   24.37   23.94    25.9   26.05   26.01   28.52   29.38   28.65   28.95
   28.71    28.6   28.86   28.66   29.03   29.53   29.33   29.93   29.93   29.47
   29.33   30.03   29.83   29.13   29.17   29.43   29.53   29.25   29.03   29.63
   28.13   27.98   27.73   27.63   28.43   27.83   28.13   27.93   29.33   28.63
   29.43   28.93   28.69   28.67   28.63   29.63   28.93   29.23   29.43   30.23
Abutment Skew #Up #Dn= , 2 , 2
  4977.7  4978.8
   25.97   23.59
  4977.7  4978.8
    25.9   23.52
Abutment Skew #Up #Dn= , 2 , 2
  5024.2 5027.69
   24.55   26.08
  5024.2 5027.69
   24.48   26.01
BR Coef= 1 , 1 , 0 ,1.25, 0 ,,,0.8,0,2,0,
WSPro=,,,, 1 ,,,, 0 ,,,, 0 ,,,,-1 ,-1 ,-1 , 0 , 0 , 0 , 0 , 0
BR U #Sta/Elev= 104
  4454.6    31.9    4458    31.9  4589.6   31.52    4598    31.5  4639.6   29.53
    4653    28.9  4736.4   28.72  4781.6   29.21    4804   29.29    4827   29.38
    4856   29.02    4879   28.74    4904   28.67  4933.4   28.59  4960.6   28.34
 4968.99   28.18  4969.1   28.18 4969.21   28.18  4971.1   28.14  4976.8   24.44
  4977.7   24.06 4977.81   24.01  4977.9   23.97  4978.8   23.59  4984.4   21.19
    4993   17.52  4994.1   14.91  4994.4   14.46  4999.8   14.41  5004.5   14.73
  5005.9   14.98  5006.4   15.03    5007   16.99  5024.1   24.51  5024.2   24.55
 5027.49   26.08  5027.6   26.13  5027.7   26.18 5030.99    27.7  5031.1   27.75
 5031.21   27.81  5032.9   28.59  5034.2   28.62  5068.8   29.45  5128.3   28.72
  5138.4   28.78  5182.6   29.02  5242.1   28.79  5244.6   28.78  5293.9   28.67
    5334   28.93  5334.3   28.73  5338.2   28.82  5349.9    29.1  5364.9    29.6
  5688.7   29.41  5703.7    29.4  5704.9    29.4  5729.9      30  5763.8      30
  5772.7      30  5958.8   29.54  6017.7    29.4  6042.7    30.1  6052.7    29.9
  6062.7    29.2  6068.8   29.21  6078.8   29.24  6084.6   29.25  6192.7    29.5
  6362.7    29.6  6373.8   29.32  6382.7    29.1  6402.7    29.7  6403.8    29.7
  6762.7    28.2  6768.8   28.05  6778.8    27.8  6782.7    27.7  6822.7    28.5
  6868.8   28.27  6873.8   28.24  6908.8   28.07  6918.8   28.02  6942.7    27.9
  6953.8   27.92  7117.7    28.2  7132.7      28  7182.7    29.4  7483.8   28.73
  7497.7    28.7  7837.7    29.5  7862.7      29  7978.8   28.76  7988.8   28.74
  8007.7    28.7  8157.7    29.7  8163.8   29.49  8173.8   29.14  8177.7      29
  8227.7    29.3  8228.8   29.34  8233.8    29.5  8257.7    30.3
BR U #Mann= 6
  4454.6      .2  4454.6      .1  4971.1    .015  5032.9      .1  5049.6      .1
  6084.6      .2
BR U Banks=4971.1,5032.9
BR D #Sta/Elev= 104
  4454.6   31.83    4458   31.83  4589.6   31.45    4598   31.43  4639.6   29.46
    4653   28.83  4736.4   28.65  4781.6   29.14    4804   29.22    4827   29.31
    4856   28.95    4879   28.67    4904    28.6  4933.4   28.52  4960.6   28.27
 4968.99   28.11  4969.1   28.11 4969.21   28.11  4971.1   28.07  4976.8   24.37
  4977.7   23.99 4977.81   23.94  4977.9    23.9  4978.8   23.52  4984.4   21.12
    4993   17.45  4994.1   14.84  4994.4   14.39  4999.8   14.34  5004.5   14.66
  5005.9   14.91  5006.4   14.96    5007   16.92  5024.1   24.44  5024.2   24.48
 5027.49   26.01  5027.6   26.06  5027.7   26.11 5030.99   27.63  5031.1   27.68
 5031.21   27.74  5032.9   28.52  5034.2   28.55  5068.8   29.38  5128.3   28.65
  5138.4   28.71  5182.6   28.95  5242.1   28.72  5244.6   28.71  5293.9    28.6
    5334   28.86  5334.3   28.66  5338.2   28.75  5349.9   29.03  5364.9   29.53
  5688.7   29.34  5703.7   29.33  5704.9   29.33  5729.9   29.93  5763.8   29.93
  5772.7   29.93  5958.8   29.47  6017.7   29.33  6042.7   30.03  6052.7   29.83
  6062.7   29.13  6068.8   29.14  6078.8   29.17  6084.6   29.18  6192.7   29.43
  6362.7   29.53  6373.8   29.25  6382.7   29.03  6402.7   29.63  6403.8   29.63
  6762.7   28.13  6768.8   27.98  6778.8   27.73  6782.7   27.63  6822.7   28.43
  6868.8    28.2  6873.8   28.17  6908.8      28  6918.8   27.95  6942.7   27.83
  6953.8   27.85  7117.7   28.13  7132.7   27.93  7182.7   29.33  7483.8   28.66
  7497.7   28.63  7837.7   29.43  7862.7   28.93  7978.8   28.69  7988.8   28.67
  8007.7   28.63  8157.7   29.63  8163.8   29.42  8173.8   29.07  8177.7   28.93
  8227.7   29.23  8228.8   29.27  8233.8   29.43  8257.7   30.23
BR D #Mann= 6
  4454.6      .2  4454.6      .1  4971.1    .015  5032.9      .1  5049.6      .1
  6084.6      .2
BR D Banks=4971.1,5032.9
BC Design=,, 0 ,, 0 ,,,,,,
BC HTab HWMax=31.91
BC Use User HTab Curves=0
BC User HTab FreeFlow(D)= 0

Type RM Length L Ch R = 1 ,2134.7  ,218.3,218.3,218.3
BEGIN DESCRIPTION:
Downstream Section of Bridge/Culvert/Weir
END DESCRIPTION:
XS GIS Cut Line= 6
      3160683.92     13810596.93      3160996.52     13810363.25
      3161096.81     13810245.39      3161245.67     13810064.71
      3161602.75     13809672.93      3163242.56     13807793.98
#Sta/Elev= 30
  4454.6   31.83    4598   31.43    4653   28.83    4827   29.31  4971.1   28.07
  4976.8   24.37    4993   17.45  4994.4   14.39  4999.8   14.34  5006.4   14.96
    5007   16.92  5032.9   28.52  5068.8   29.38  5293.9    28.6  5364.9   29.53
  5729.9   29.93  6017.7   29.33  6042.7   30.03  6084.6   29.18  6403.8   29.63
  6782.7   27.63  6822.7   28.43  7132.7   27.93  7182.7   29.33  7497.7   28.63
  7837.7   29.43  8007.7   28.63  8157.7   29.63  8227.7   29.23  8257.7   30.23
#Mann= 6 , 1 , 0
  4454.6      .2       0  4454.6      .1       0  4971.1    .015       0
  5032.9      .1       0  5049.6      .1       0  6084.6      .2       0
#XS Ineff= 2 , 0
       0  4967.6    28.4  5037.2       0    28.5
Permanent Ineff=
       F       F
Bank Sta=4971.1,5032.9
XS Rating Curve= 0 ,0
Exp/Cntr=0.5,0.3