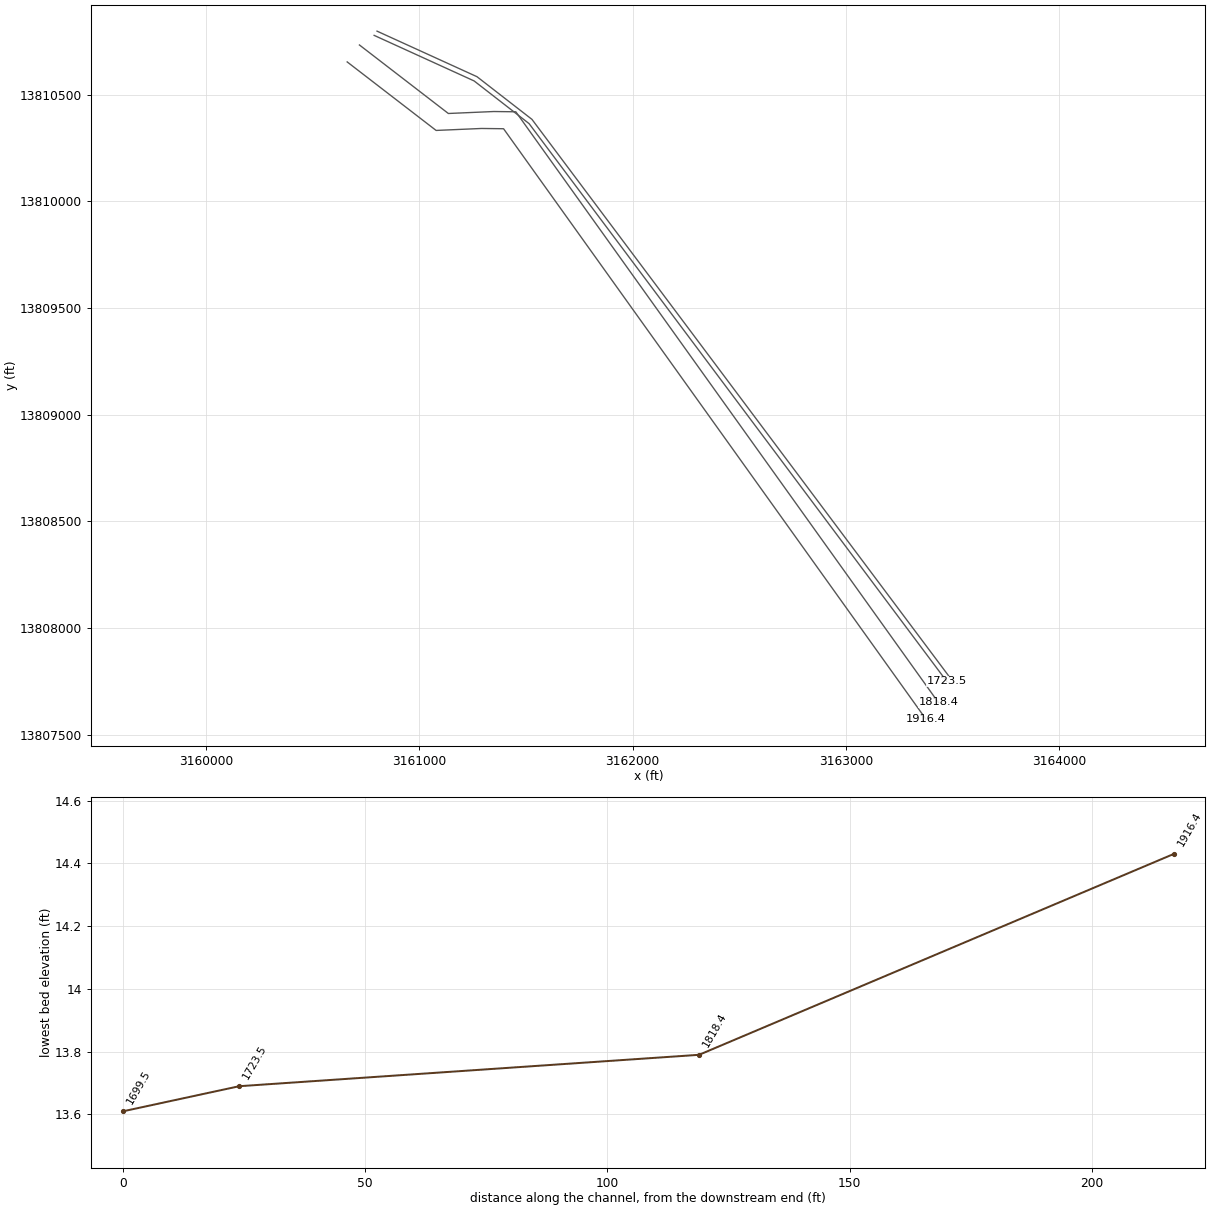
HEC-RAS study C106-03-00.PRJ: C106-03-00

--- C106-03-00.g01 (geometry) --- (continued)

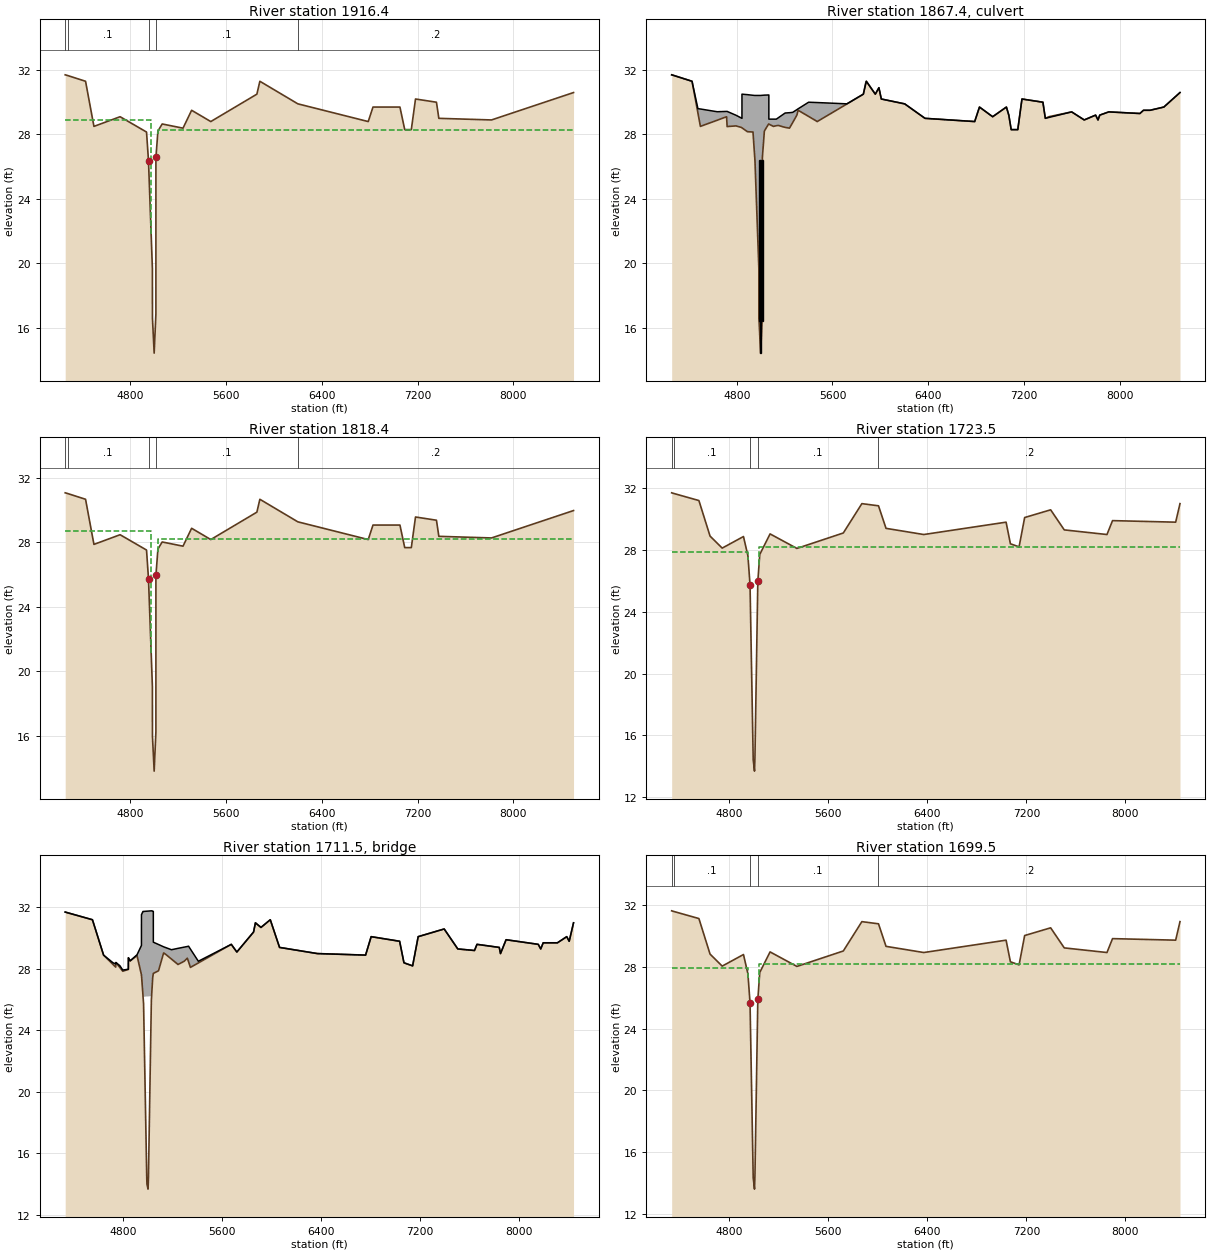
Type RM Length L Ch R = 1 ,1916.4  ,98,98,98
BEGIN DESCRIPTION:
Upstream Section of Bridge/Culvert/Weir
END DESCRIPTION:
XS GIS Cut Line= 5
       3160662.8     13810653.18      3161079.52     13810332.09
      3161292.18     13810341.31      3161395.65     13810340.07
      3163375.93     13807571.87
#Sta/Elev= 30
  4256.9    31.7  4280.1   31.65  4426.9    31.3  4496.9    28.5  4715.5    29.1
 4936.19   28.15 4952.66   26.36 4985.14   19.68 4985.68   16.61    5000   14.43
  5014.4   16.86 5014.63   26.57 5031.25   28.21 5066.95   28.65 5240.91   28.39
  5312.9    29.5  5472.9    28.8  5857.9    30.5  5882.9    31.3  6200.1    29.9
  6787.9    28.8  6827.9    29.7  7052.9    29.7  7092.9    28.3  7147.9    28.3
  7182.9    30.2  7357.9      30  7377.9      29  7817.9    28.9  8502.9    30.6
#Mann= 5 , 1 , 0
  4256.9      .2       0  4280.1      .1       0 4952.66    .015       0
 5014.63      .1       0  6200.1      .2       0
#XS Ineff= 2 , 0
       0    4975    28.9  5029.2       0    28.3
Permanent Ineff=
       F       F
Bank Sta=4952.66,5014.63
XS Rating Curve= 0 ,0
Exp/Cntr=0.5,0.3

Type RM Length L Ch R = 2 ,1867.4  ,,,
BEGIN DESCRIPTION:
WINKLER DRIVE, SKEW ANGLE OF 40 DEGREES
Structure ID: C63-5
END DESCRIPTION:
Bridge Culvert--1,0,-1,-1, 0
Deck Dist Width WeirC Skew NumUp NumDn MinLoCord MaxHiCord MaxSubmerge Is_Ogee
10,78,3,0, 60, 60, , , 0.95, 0, 1,1,,
  4256.9  4426.9  4476.2  4496.9  4636.7  4715.5 4720.03 4794.64 4843.89    4844
    4890 4936.19 4952.66 4985.14 4985.68    5000  5014.4 5014.63 5031.25 5066.95
  5068.7 5068.81 5106.93    5131  5204.5 5240.91  5267.3  5302.9  5312.9  5400.5
  5472.9  5720.5  5857.9  5882.9  5957.9  5987.9  6007.9  6202.9  6372.9  6787.9
  6827.9  6937.9  7052.9  7072.9  7092.9  7147.9  7182.9  7357.9  7377.9  7597.9
  7702.9  7797.9  7817.9  7832.9  7907.9  8167.9  8197.9  8252.9  8367.9  8502.9
    31.7    31.3    29.6   29.58   29.41   29.43   29.43   29.19      29    30.5
   30.47   30.43   30.42   30.42   30.42   30.42   30.43   30.43   30.44   30.45
   30.45   28.95   28.95   28.95   29.33   29.35   29.37   29.54   29.59      30
   29.98    29.9    30.5    31.3    30.5    30.9    30.2    29.9      29    28.8
    29.7    29.1    29.7    29.2    28.3    28.3    30.2      30      29    29.4
    28.9    29.2    28.9    29.2    29.4    29.3    29.5    29.5    29.7    30.6
    31.7    31.3   29.33    28.5   28.88    29.1   28.49   28.53   28.41   28.41
   28.17   28.15   26.36   19.68   16.61   14.43   16.86   26.57   28.21   28.65
   28.64   28.64    28.5   28.54   28.44   28.39   28.73    29.2    29.5   29.12
    28.8   29.89    30.5    31.3    30.5    30.9    30.2    29.9      29    28.8
    29.7    29.1    29.7    29.2    28.3    28.3    30.2      30      29    29.4
    28.9    29.2    28.9    29.2    29.4    29.3    29.5    29.5    29.7    30.6
  4256.9  4426.9  4476.2  4496.9  4636.7  4715.5 4720.03 4794.64 4843.89    4844
    4890 4936.19 4952.66 4985.14 4985.68    5000  5014.4 5014.63 5031.25 5066.95
  5068.7 5068.81 5106.93    5131  5204.5 5240.91  5267.3  5302.9  5312.9  5400.5
  5472.9  5720.5  5857.9  5882.9  5957.9  5987.9  6007.9  6202.9  6372.9  6787.9
  6827.9  6937.9  7052.9  7072.9  7092.9  7147.9  7182.9  7357.9  7377.9  7597.9
  7702.9  7797.9  7817.9  7832.9  7907.9  8167.9  8197.9  8252.9  8367.9  8502.9
    31.7    31.3    29.6   29.58   29.41   29.43   29.43   29.19      29    30.5
   30.47   30.43   30.42   30.42   30.42   30.42   30.43   30.43   30.44   30.45
   30.45   28.95   28.95   28.95   29.33   29.35   29.37   29.54   29.59      30
   29.98    29.9    30.5    31.3    30.5    30.9    30.2    29.9      29    28.8
    29.7    29.1    29.7    29.2    28.3    28.3    30.2      30      29    29.4
    28.9    29.2    28.9    29.2    29.4    29.3    29.5    29.5    29.7    30.6
   31.07   30.67    28.7   27.87   28.25   28.47   27.86    27.9   27.78   27.78
   27.54   27.52   25.73   19.05   15.98    13.8   16.23   25.94   27.58   28.02
   28.01   28.01   27.87   27.91   27.81   27.76    28.1   28.57   28.87   28.49
   28.17   29.26   29.87   30.67   29.87   30.27   29.57   29.27   28.37   28.17
   29.07   28.47   29.07   28.57   27.67   27.67   29.57   29.37   28.37   28.77
   28.27   28.57   28.27   28.57   28.77   28.67   28.87   28.87   29.07   29.97
BR Coef= 1 , 0 , 0 ,1.25, 0 ,,,0.8,-1,2,0,
WSPro=,,,, 1 ,,,, 0 ,,,, 0 ,,,,-1 ,-1 ,-1 , 0 , 0 , 0 , 0 , 0
Culvert=2,10,10,78,0.015,0.9,1,8,1,16.43,4990,16.15,4990,Culvert #1  , 0 ,10
Culvert Bottom n=0.015
Culvert=2,12,10,78,0.015,0.9,1,8,1,14.43,5001.9,14.15,5001.9,Culvert #2  , 0 ,10
Culvert Bottom n=0.015
Culvert=2,10,10,78,0.015,0.9,1,8,1,16.43,5014.3,16.15,5014.3,Culvert #3  , 0 ,10
Culvert Bottom n=0.015
BR U #Sta/Elev= 73
  4256.9    31.7  4280.1   31.65  4426.9    31.3  4476.2   29.33  4496.9    28.5
  4636.7   28.88  4715.5    29.1 4720.03   28.49  4737.2    28.5 4794.64   28.53
  4840.9   28.43    4841   28.43 4843.89   28.41    4844   28.41 4844.11   28.41
    4890   28.17 4936.19   28.15 4952.66   26.36  4965.6    23.7 4985.14   19.68
 4985.68   16.61    5000   14.43  5014.4   16.86 5014.63   26.57 5031.25   28.21
  5061.1   28.58 5066.95   28.65 5068.59   28.64  5068.7   28.64 5068.81   28.64
 5106.93    28.5    5131   28.54 5148.07   28.56 5192.65   28.46  5204.5   28.44
 5240.91   28.39  5267.3   28.73  5302.9    29.2  5312.9    29.5  5400.5   29.12
  5472.9    28.8  5720.5   29.89  5857.9    30.5  5877.9    31.2  5882.9    31.3
  5957.9    30.5  5987.9    30.9  6007.9    30.2  6200.1    29.9  6202.9    29.9
  6372.9      29  6787.9    28.8  6827.9    29.7  6937.9    29.1  7052.9    29.7
  7072.9    29.2  7092.9    28.3  7147.9    28.3  7182.9    30.2  7357.9      30
  7377.9      29  7407.9    29.1  7597.9    29.4  7702.9    28.9  7797.9    29.2
  7817.9    28.9  7832.9    29.2  7907.9    29.4  8167.9    29.3  8197.9    29.5
  8252.9    29.5  8367.9    29.7  8502.9    30.6
BR U #Mann= 5
  4256.9      .2  4280.1      .1 4952.66    .015 5014.63      .1  6200.1      .2
BR U Banks=4952.66,5014.63
BR D #Sta/Elev= 73
  4256.9   31.07  4280.1   31.02  4426.9   30.67  4476.2    28.7  4496.9   27.87
  4636.7   28.25  4715.5   28.47 4720.03   27.86  4737.2   27.87 4794.64    27.9
  4840.9    27.8    4841    27.8 4843.89   27.78    4844   27.78 4844.11   27.78
    4890   27.54 4936.19   27.52 4952.66   25.73  4965.6   23.07 4985.14   19.05
 4985.68   15.98    5000    13.8  5014.4   16.23 5014.63   25.94 5031.25   27.58
  5061.1   27.95 5066.95   28.02 5068.59   28.01  5068.7   28.01 5068.81   28.01
 5106.93   27.87    5131   27.91 5148.07   27.93 5192.65   27.83  5204.5   27.81
 5240.91   27.76  5267.3    28.1  5302.9   28.57  5312.9   28.87  5400.5   28.49
  5472.9   28.17  5720.5   29.26  5857.9   29.87  5877.9   30.57  5882.9   30.67
  5957.9   29.87  5987.9   30.27  6007.9   29.57  6200.1   29.27  6202.9   29.27
  6372.9   28.37  6787.9   28.17  6827.9   29.07  6937.9   28.47  7052.9   29.07
  7072.9   28.57  7092.9   27.67  7147.9   27.67  7182.9   29.57  7357.9   29.37
  7377.9   28.37  7407.9   28.47  7597.9   28.77  7702.9   28.27  7797.9   28.57
  7817.9   28.27  7832.9   28.57  7907.9   28.77  8167.9   28.67  8197.9   28.87
  8252.9   28.87  8367.9   29.07  8502.9   29.97
BR D #Mann= 5
  4256.9      .2  4280.1      .1 4952.66    .015 5014.63      .1  6200.1      .2
BR D Banks=4952.66,5014.63
BC Design=,, 0 ,, 0 ,,,,,,
BC HTab HWMax=31.7
BC Use User HTab Curves=0
BC User HTab FreeFlow(D)= 0

Type RM Length L Ch R = 1 ,1818.4  ,94.9,94.9,94.9
BEGIN DESCRIPTION:
Downstream Section of Bridge/Culvert/Weir
END DESCRIPTION:
XS GIS Cut Line= 5
      3160720.22     13810732.59      3161136.94     13810411.51
       3161349.6     13810420.73      3161453.07     13810419.49
      3163433.35     13807651.29
#Sta/Elev= 30
  4256.9   31.06  4280.1   31.01  4426.9   30.66  4496.9   27.86  4715.5   28.46
 4936.19   27.51 4952.66   25.72 4985.14   19.04 4985.68   15.97    5000   13.79
  5014.4   16.22 5014.63   25.93 5031.25   27.57 5066.95   28.01 5240.91   27.75
  5312.9   28.86  5472.9   28.16  5857.9   29.86  5882.9   30.66  6200.1   29.26
  6787.9   28.16  6827.9   29.06  7052.9   29.06  7092.9   27.66  7147.9   27.66
  7182.9   29.56  7357.9   29.36  7377.9   28.36  7817.9   28.26  8502.9   29.96
#Mann= 5 , 1 , 0
  4256.9      .2       0  4280.1      .1       0 4952.66    .015       0
 5014.63      .1       0  6200.1      .2       0
#XS Ineff= 2 , 0
       0    4975    28.7  5029.2       0    28.2
Permanent Ineff=
       F       F
Bank Sta=4952.66,5014.63
XS Rating Curve= 0 ,0
Exp/Cntr=0.5,0.3

Type RM Length L Ch R = 1 ,1723.5  ,24,24,24
BEGIN DESCRIPTION:
Upstream Section of Bridge/Culvert/Weir
END DESCRIPTION:
XS GIS Cut Line= 4
      3160789.12     13810777.59       3161257.7     13810564.04
      3161515.23     13810364.12      3163472.74     13807749.94
#Sta/Elev= 30
  4334.3   31.71  4355.2   31.66  4554.3   31.21  4644.3   28.91  4742.5   28.13
  4914.4   28.88  4950.3   27.63  4967.4   25.75  4993.1   14.41  5003.5   13.69
  5006.9   14.51  5030.3   25.97    5046   27.72  5129.3   29.05    5346   28.11
    5721   29.11    5871   31.01  6005.2   30.87    6066   29.41    6371   29.01
    7036   29.81    7071   28.41    7141   28.21    7186   30.11    7396   30.61
    7506   29.31    7851   29.01    7896   29.91    8406   29.81    8441   31.01
#Mann= 5 , 1 , 0
  4334.3      .2       0  4355.2      .1       0  4967.4    .015       0
  5030.3      .1       0  6005.2      .2       0
#XS Ineff= 2 , 0
       0    4953    27.9    5040       0    28.2
Permanent Ineff=
       F       F
Bank Sta=4967.4,5030.3
XS Rating Curve= 0 ,0
Exp/Cntr=0.5,0.3

Type RM Length L Ch R = 3 ,1711.5  ,,,
BEGIN DESCRIPTION:
GALVESTON ROAD PEDESTRIAN BRIDGE
Structure ID: C63-4
END DESCRIPTION:
Bridge Culvert--1,0,-1,-1, 0
Deck Dist Width WeirC Skew NumUp NumDn MinLoCord MaxHiCord MaxSubmerge Is_Ogee
10,4,2.6,0, 58, 58, , , 0.95, 0, 1,1,,
  4334.3  4554.3  4644.3  4720.7  4742.5  4744.1    4776  4799.3  4844.4  4844.9
  4859.3  4914.4  4950.3  4950.4  4962.7  4967.4  5030.3  5033.9  5041.2  5046.2
 5046.31  5088.2  5129.3  5192.8  5245.6    5296    5321    5331    5346    5410
    5676    5721    5856    5871    5916    5991    6066    6371    6761    6806
    7036    7071    7141    7186    7396    7506    7641    7661    7841    7851
    7896    8156    8176    8196    8311    8386    8406    8441
    31.7    31.2    28.9    28.4   28.33   28.42   28.21   27.93   27.98   28.73
   28.53   28.92   29.53   31.53   31.74   31.74   31.78   31.78   31.76   31.74
   29.74   29.59   29.44   29.25   29.34   29.42   29.46   29.48   29.29    28.5
    29.6    29.1    30.4      31    30.7    31.2    29.4      29    28.9    30.1
    29.8    28.4    28.2    30.1    30.6    29.3    29.2    29.6    29.4      29
    29.9    29.6    29.3    29.7    29.7    30.1    29.8      31
    31.7    31.2    28.9   28.29   28.12   28.41   28.09   27.85   27.97   28.72
   28.52   28.87   27.62   27.61   26.26   26.19   26.23   26.44   27.42   27.71
   27.71   27.88   29.04   28.64   28.29    28.5    28.7   28.46    28.1   28.39
    29.6    29.1    30.4      31    30.7    31.2    29.4      29    28.9    30.1
    29.8    28.4    28.2    30.1    30.6    29.3    29.2    29.6    29.4      29
    29.9    29.6    29.3    29.7    29.7    30.1    29.8      31
  4334.3  4554.3  4644.3  4720.7  4742.5  4744.1    4776  4799.3  4844.4  4844.9
  4859.3  4914.4  4950.3  4950.4  4962.7  4967.4  5030.3  5033.9  5041.2  5046.2
 5046.31  5088.2  5129.3  5192.8  5245.6    5296    5321    5331    5346    5410
    5676    5721    5856    5871    5916    5991    6066    6371    6761    6806
    7036    7071    7141    7186    7396    7506    7641    7661    7841    7851
    7896    8156    8176    8196    8311    8386    8406    8441
    31.7    31.2    28.9    28.4   28.33   28.42   28.21   27.93   27.98   28.73
   28.53   28.92   29.53   31.53   31.74   31.74   31.78   31.78   31.76   31.74
   29.74   29.59   29.44   29.25   29.34   29.42   29.46   29.48   29.29    28.5
    29.6    29.1    30.4      31    30.7    31.2    29.4      29    28.9    30.1
    29.8    28.4    28.2    30.1    30.6    29.3    29.2    29.6    29.4      29
    29.9    29.6    29.3    29.7    29.7    30.1    29.8      31
   31.54   31.04   28.74   28.13   27.96   28.25   27.93   27.69   27.81   28.56
   28.36   28.71   27.46   27.45    26.1   26.03   26.07   26.28   27.26   27.55
   27.55   27.72   28.88   28.48   28.13   28.34   28.54    28.3   27.94   28.23
   29.44   28.94   30.24   30.84   30.54   31.04   29.24   28.84   28.74   29.94
   29.64   28.24   28.04   29.94   30.44   29.14   29.04   29.44   29.24   28.84
   29.74   29.44   29.14   29.54   29.54   29.94   29.64   30.84
Abutment Skew #Up #Dn= , 2 , 2
  4962.7    4992
   26.23   14.93
  4962.7    4992
   26.07   14.77
Abutment Skew #Up #Dn= , 2 , 2
  5007.4 5033.99
   14.74   26.43
  5007.4 5033.99
   14.58   26.27
BR Coef= 1 , 1 , 0 ,1.25, 0 ,,,0.8,0,2,0,
WSPro=,,,, 1 ,,,, 0 ,,,, 0 ,,,,-1 ,-1 ,-1 , 0 , 0 , 0 , 0 , 0
BR U #Sta/Elev= 81
  4334.3    31.7  4355.2   31.65  4554.3    31.2  4644.3    28.9  4720.7   28.29
  4742.5   28.12  4744.1   28.41    4776   28.09  4799.3   27.85  4829.1   27.93
  4844.4   27.97  4844.9   28.72  4851.4   28.63  4859.3   28.52  4914.4   28.87
 4950.19   27.62  4950.3   27.62  4950.4   27.61 4950.51    27.6  4962.7   26.26
 4962.81   26.24  4962.9   26.23  4967.4   25.74  4991.9   14.98    4992   14.93
  4993.1    14.4  4994.6   14.02  5003.5   13.68  5005.6   14.12  5006.9    14.5
  5007.3   14.69  5007.4   14.74  5030.3   25.96 5033.79   26.43  5033.9   26.44
    5034   26.46  5041.2   27.42    5046   27.71 5046.09   27.71  5046.2   27.71
 5046.31   27.71  5088.2   27.88  5129.3   29.04  5137.2      29  5144.6   28.96
  5192.8   28.64  5245.6   28.29    5296    28.5    5321    28.7    5331   28.46
    5346    28.1    5410   28.39    5676    29.6    5721    29.1    5856    30.4
    5871      31    5916    30.7    5991    31.2  6005.2   30.86    6066    29.4
    6371      29    6761    28.9    6806    30.1    7036    29.8    7071    28.4
    7141    28.2    7186    30.1    7396    30.6    7506    29.3    7641    29.2
    7661    29.6    7841    29.4    7851      29    7896    29.9    8156    29.6
    8176    29.3    8196    29.7    8311    29.7    8386    30.1    8406    29.8
    8441      31
BR U #Mann= 5
  4334.3      .2  4355.2      .1  4967.4    .015  5030.3      .1  6005.2      .2
BR U Banks=4967.4,5030.3
BR D #Sta/Elev= 81
  4334.3   31.54  4355.2   31.49  4554.3   31.04  4644.3   28.74  4720.7   28.13
  4742.5   27.96  4744.1   28.25    4776   27.93  4799.3   27.69  4829.1   27.77
  4844.4   27.81  4844.9   28.56  4851.4   28.47  4859.3   28.36  4914.4   28.71
 4950.19   27.46  4950.3   27.46  4950.4   27.45 4950.51   27.44  4962.7    26.1
 4962.81   26.08  4962.9   26.07  4967.4   25.58  4991.9   14.82    4992   14.77
  4993.1   14.24  4994.6   13.86  5003.5   13.52  5005.6   13.96  5006.9   14.34
  5007.3   14.53  5007.4   14.58  5030.3    25.8 5033.79   26.27  5033.9   26.28
    5034    26.3  5041.2   27.26    5046   27.55 5046.09   27.55  5046.2   27.55
 5046.31   27.55  5088.2   27.72  5129.3   28.88  5137.2   28.84  5144.6    28.8
  5192.8   28.48  5245.6   28.13    5296   28.34    5321   28.54    5331    28.3
    5346   27.94    5410   28.23    5676   29.44    5721   28.94    5856   30.24
    5871   30.84    5916   30.54    5991   31.04  6005.2    30.7    6066   29.24
    6371   28.84    6761   28.74    6806   29.94    7036   29.64    7071   28.24
    7141   28.04    7186   29.94    7396   30.44    7506   29.14    7641   29.04
    7661   29.44    7841   29.24    7851   28.84    7896   29.74    8156   29.44
    8176   29.14    8196   29.54    8311   29.54    8386   29.94    8406   29.64
    8441   30.84
BR D #Mann= 5
  4334.3      .2  4355.2      .1  4967.4    .015  5030.3      .1  6005.2      .2
BR D Banks=4967.4,5030.3
BC Design=,, 0 ,, 0 ,,,,,,
BC HTab HWMax=31.71
BC Use User HTab Curves=0
BC User HTab FreeFlow(D)= 0

Type RM Length L Ch R = 1 ,1699.5  ,27.3,27.3,27.3
BEGIN DESCRIPTION:
Downstream Section of Bridge/Culvert/Weir
END DESCRIPTION:
XS GIS Cut Line= 4
       3160802.6     13810797.45      3161271.18      13810583.9
      3161528.71     13810383.98      3163486.22      13807769.8
#Sta/Elev= 30
  4334.3   31.63  4355.2   31.58  4554.3   31.13  4644.3   28.83  4742.5   28.05
  4914.4    28.8  4950.3   27.55  4967.4   25.67  4993.1   14.33  5003.5   13.61
  5006.9   14.43  5030.3   25.89    5046   27.64  5129.3   28.97    5346   28.03
    5721   29.03    5871   30.93  6005.2   30.79    6066   29.33    6371   28.93
    7036   29.73    7071   28.33    7141   28.13    7186   30.03    7396   30.53
    7506   29.23    7851   28.93    7896   29.83    8406   29.73    8441   30.93
#Mann= 5 , 1 , 0
  4334.3      .2       0  4355.2      .1       0  4967.4    .015       0
  5030.3      .1       0  6005.2      .2       0
#XS Ineff= 2 , 0
       0    4953    27.9    5040       0    28.2
Permanent Ineff=
       F       F
Bank Sta=4967.4,5030.3
XS Rating Curve= 0 ,0
Exp/Cntr=0.5,0.3