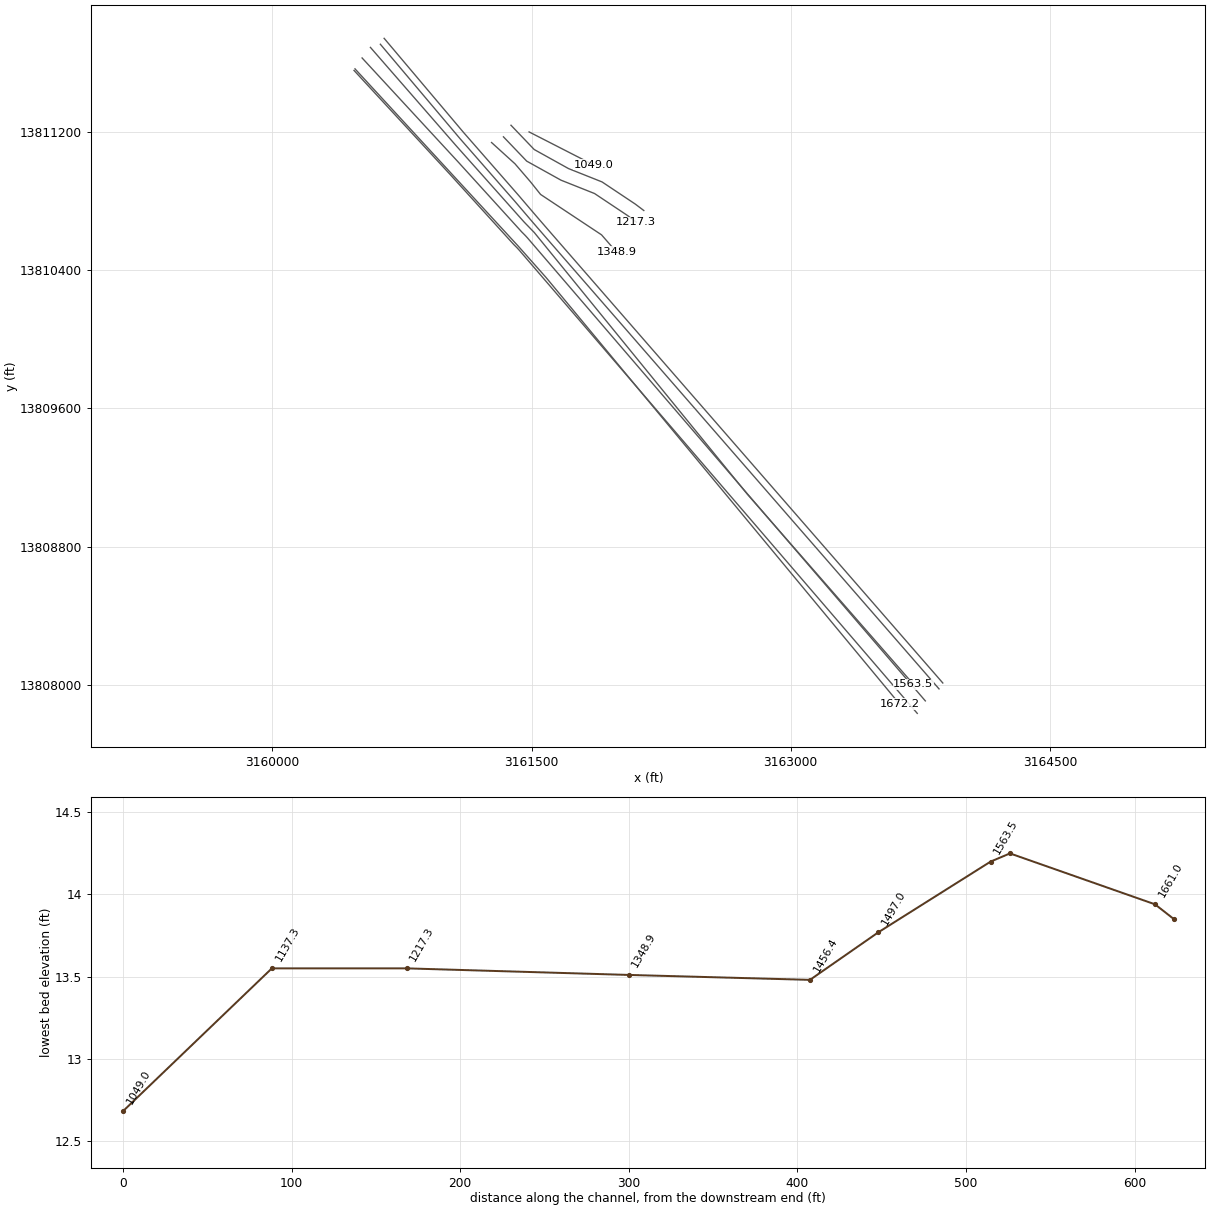
HEC-RAS study C106-03-00.PRJ: C106-03-00

--- C106-03-00.g01 (geometry) --- (continued)

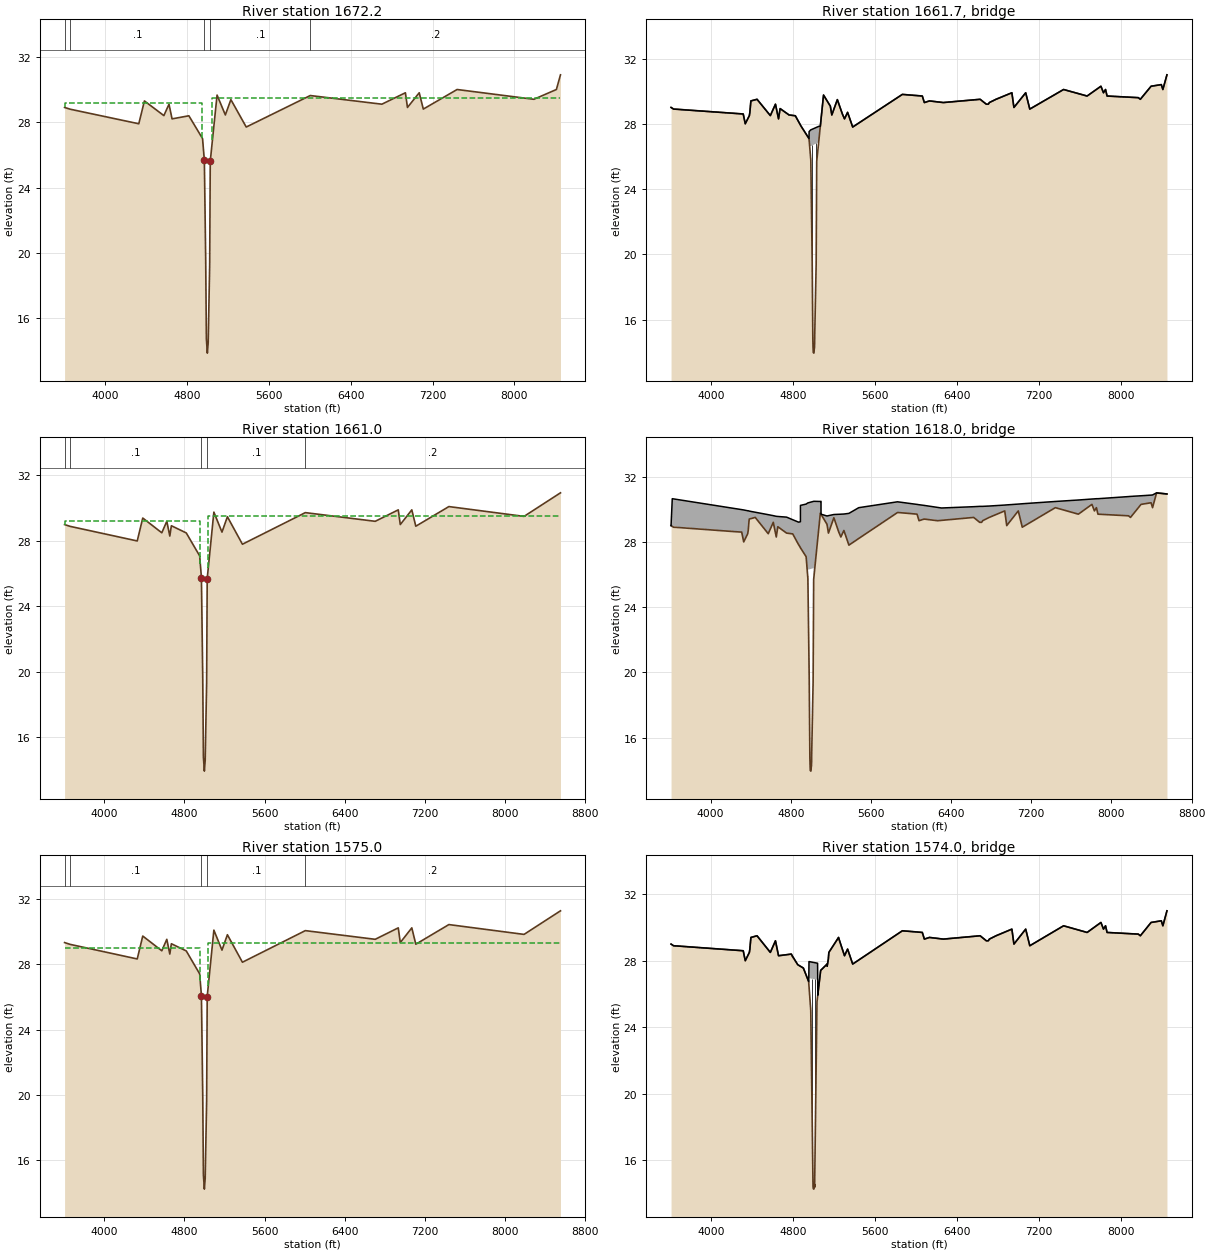
Type RM Length L Ch R = 1 ,1672.2  ,11.2,11.2,11.2
BEGIN DESCRIPTION:
Upstream Section of Bridge/Culvert/Weir
END DESCRIPTION:
XS GIS Cut Line= 4
      3160477.98     13811565.94      3161425.09     13810537.34
       3161584.3     13810357.84      3163630.32     13807889.02
#Sta/Elev= 30
  3605.2   28.91  3661.5    28.8  4330.2   27.91  4385.2   29.31  4575.2   28.41
  4625.2   29.11  4655.2   28.21 4819.44    28.4 4953.04      27 4970.64   25.67
 4983.84   19.55 4990.44   14.72 5000.04   13.85 5008.14   14.49 5022.74    19.3
 5028.34   25.61 5094.84   29.67 5175.74   28.45 5229.84   29.39  5379.8   27.71
  6005.2   29.64  6704.8   29.11  6934.8   29.81  6954.8   28.91  7069.8   29.81
  7109.8   28.81  7439.8   30.01  8189.8   29.41  8409.8   30.01  8449.8   30.91
#Mann= 5 , 1 , 0
  3605.2      .2       0  3661.5      .1       0 4970.64    .015       0
 5028.34      .1       0  6005.2      .2       0
#XS Ineff= 2 , 0
       0  4949.3    29.2  5049.4       0    29.5
Permanent Ineff=
       F       F
Bank Sta=4970.64,5028.34
XS Rating Curve= 0 ,0
Exp/Cntr=0.5,0.3

Type RM Length L Ch R = 3 ,1661.7  ,,,
BEGIN DESCRIPTION:
PIPELINE U/S OF GALVESTON ROAD
END DESCRIPTION:
Bridge Culvert--1,0,-1,-1, 0
Deck Dist Width WeirC Skew NumUp NumDn MinLoCord MaxHiCord MaxSubmerge Is_Ogee
10,1,2.6,0, 55, 55, , , 0.95, 0, 1,1,,
  3605.2  3630.2  4310.2  4330.2  4370.2  4375.2  4385.2  4445.2  4575.2  4625.2
  4655.2 4670.64 4757.94 4819.44 4875.64 4953.04 4953.74 4958.74 4968.44 5047.53
 5063.54 5094.84 5161.14 5175.74 5229.84 5278.84  5299.8  5329.8  5379.8  5864.8
  6059.8  6079.8  6129.8  6264.8  6624.8  6684.8  6704.8  6714.8  6779.8  6934.8
  6954.8  7069.8  7109.8  7439.8  7669.8  7804.8  7829.8  7849.8  7864.8  8169.8
  8189.8  8294.8  8394.8  8409.8  8449.8
      29    28.9    28.6      28    28.5    28.7    29.4    29.5    28.5    29.2
    28.3   28.93   28.54   28.49   27.85   27.09   27.52   27.55   27.62   27.84
   27.85   29.76   29.08   28.54   29.48    28.6    28.3    28.7    27.8    29.8
    29.7    29.3    29.4    29.3    29.5    29.2    29.2    29.3    29.5    29.9
      29    29.9    28.9    30.1    29.7    30.3    29.9    30.1    29.7    29.6
    29.5    30.3    30.4    30.1      31
      29    28.9    28.6      28    28.5    28.7    29.4    29.5    28.5    29.2
    28.3   28.93   28.54   28.49   27.85   27.09   27.04   26.66   26.62   26.87
   27.85   29.76   29.08   28.54   29.48    28.6    28.3    28.7    27.8    29.8
    29.7    29.3    29.4    29.3    29.5    29.2    29.2    29.3    29.5    29.9
      29    29.9    28.9    30.1    29.7    30.3    29.9    30.1    29.7    29.6
    29.5    30.3    30.4    30.1      31
  3605.2  3630.2  4310.2  4330.2  4370.2  4375.2  4385.2  4445.2  4575.2  4625.2
  4655.2 4670.64 4757.94 4819.44 4875.64 4953.04 4953.74 4958.74 4968.44 5047.53
 5063.54 5094.84 5161.14 5175.74 5229.84 5278.84  5299.8  5329.8  5379.8  5864.8
  6059.8  6079.8  6129.8  6264.8  6624.8  6684.8  6704.8  6714.8  6779.8  6934.8
  6954.8  7069.8  7109.8  7439.8  7669.8  7804.8  7829.8  7849.8  7864.8  8169.8
  8189.8  8294.8  8394.8  8409.8  8449.8
      29    28.9    28.6      28    28.5    28.7    29.4    29.5    28.5    29.2
    28.3   28.93   28.54   28.49   27.85   27.09   27.52   27.55   27.62   27.84
   27.85   29.76   29.08   28.54   29.48    28.6    28.3    28.7    27.8    29.8
    29.7    29.3    29.4    29.3    29.5    29.2    29.2    29.3    29.5    29.9
      29    29.9    28.9    30.1    29.7    30.3    29.9    30.1    29.7    29.6
    29.5    30.3    30.4    30.1      31
      29    28.9    28.6      28    28.5    28.7    29.4    29.5    28.5    29.2
    28.3   28.93   28.54   28.49   27.85   27.09   27.04   26.66   26.62   26.87
   27.85   29.76   29.08   28.54   29.48    28.6    28.3    28.7    27.8    29.8
    29.7    29.3    29.4    29.3    29.5    29.2    29.2    29.3    29.5    29.9
      29    29.9    28.9    30.1    29.7    30.3    29.9    30.1    29.7    29.6
    29.5    30.3    30.4    30.1      31
Pier Skew, UpSta & Num, DnSta & Num=  ,4983.8, 2 ,4983.8, 2 , 0 , 0 , 0 ,,
     1.3     1.3
   18.16   27.67
     1.3     1.3
   18.16   27.67
Pier Skew, UpSta & Num, DnSta & Num=  ,5022.7, 2 ,5022.7, 2 , 0 , 0 , 0 ,,
     1.3     1.3
   18.19   27.79
     1.3     1.3
   18.19   27.79
BR Coef= 1 , 1 , 0 ,1.25, 0 ,,,0.8,0,2,0,
WSPro=,,,, 1 ,,,, 0 ,,,, 0 ,,,,-1 ,-1 ,-1 , 0 , 0 , 0 , 0 , 0
BR U #Sta/Elev= 72
  3605.2      29  3630.2    28.9  3661.5   28.89  4310.2    28.6  4330.2      28
  4370.2    28.5  4375.2    28.7  4385.2    29.4  4445.2    29.5  4575.2    28.5
  4625.2    29.2  4655.2    28.3 4670.64   28.93 4757.94   28.54 4819.44   28.49
 4875.64   27.85 4953.04   27.09 4953.74   27.04 4958.65   26.67 4958.74   26.66
 4968.44   25.93 4970.64   25.76 4983.84   19.64 4990.44   14.81 4991.94    14.4
 4994.54   13.98 5000.04   13.94 5000.24   13.94 5006.44   14.29 5008.14   14.58
 5008.74   15.01 5022.74   19.39 5028.34    25.7 5034.54   26.08 5047.53   26.87
 5047.64   26.88 5063.54   27.85 5094.84   29.76 5161.14   29.08 5175.74   28.54
 5229.84   29.48 5278.84    28.6  5299.8    28.3  5329.8    28.7  5379.8    27.8
  5864.8    29.8  6005.2   29.73  6059.8    29.7  6079.8    29.3  6129.8    29.4
  6264.8    29.3  6624.8    29.5  6684.8    29.2  6704.8    29.2  6714.8    29.3
  6779.8    29.5  6934.8    29.9  6954.8      29  7069.8    29.9  7109.8    28.9
  7439.8    30.1  7669.8    29.7  7804.8    30.3  7829.8    29.9  7849.8    30.1
  7864.8    29.7  8169.8    29.6  8189.8    29.5  8294.8    30.3  8394.8    30.4
  8409.8    30.1  8449.8      31
BR U #Mann= 5
  3605.2      .2  3661.5      .1 4970.64    .015 5028.34      .1  6005.2      .2
BR U Banks=4970.64,5028.34
BR D #Sta/Elev= 72
  3605.2      29  3630.2    28.9  3661.5   28.89  4310.2    28.6  4330.2      28
  4370.2    28.5  4375.2    28.7  4385.2    29.4  4445.2    29.5  4575.2    28.5
  4625.2    29.2  4655.2    28.3 4670.64   28.93 4757.94   28.54 4819.44   28.49
 4875.64   27.85 4953.04   27.09 4953.74   27.04 4958.65   26.67 4958.74   26.66
 4968.44   25.93 4970.64   25.76 4983.84   19.64 4990.44   14.81 4991.94    14.4
 4994.54   13.98 5000.04   13.94 5000.24   13.94 5006.44   14.29 5008.14   14.58
 5008.74   15.01 5022.74   19.39 5028.34    25.7 5034.54   26.08 5047.53   26.87
 5047.64   26.88 5063.54   27.85 5094.84   29.76 5161.14   29.08 5175.74   28.54
 5229.84   29.48 5278.84    28.6  5299.8    28.3  5329.8    28.7  5379.8    27.8
  5864.8    29.8  6005.2   29.73  6059.8    29.7  6079.8    29.3  6129.8    29.4
  6264.8    29.3  6624.8    29.5  6684.8    29.2  6704.8    29.2  6714.8    29.3
  6779.8    29.5  6934.8    29.9  6954.8      29  7069.8    29.9  7109.8    28.9
  7439.8    30.1  7669.8    29.7  7804.8    30.3  7829.8    29.9  7849.8    30.1
  7864.8    29.7  8169.8    29.6  8189.8    29.5  8294.8    30.3  8394.8    30.4
  8409.8    30.1  8449.8      31
BR D #Mann= 5
  3605.2      .2  3661.5      .1 4970.64    .015 5028.34      .1  6005.2      .2
BR D Banks=4970.64,5028.34
BC Design=,, 0 ,, 0 ,,,,,,
BC HTab HWMax=30.91
BC Use User HTab Curves=0
BC User HTab FreeFlow(D)= 0

Type RM Length L Ch R = 1 ,1661.0  ,86,86,86
BEGIN DESCRIPTION:
Upstream Section of Bridge/Culvert/Weir
END DESCRIPTION:
XS GIS Cut Line= 6
      3160472.42     13811556.71      3161026.37     13810957.02
      3161396.25     13810549.95      3161416.55     13810529.51
      3161429.96     13810514.87       3163732.6     13807835.16
#Sta/Elev= 30
  3605.2      29  3661.3   28.89  4330.2      28  4385.2    29.4  4575.2    28.5
  4625.2    29.2  4655.2    28.3  4670.6   28.93  4819.4   28.49    4953   27.09
  4970.6   25.76  4983.8   19.64  4990.4   14.81    5000   13.94  5008.1   14.58
  5022.7   19.39  5028.3    25.7  5094.8   29.76  5175.7   28.54  5229.8   29.48
  5379.8    27.8  6007.2   29.73  6704.8    29.2  6934.8    29.9  6954.8      29
  7069.8    29.9  7109.8    28.9  7439.8    30.1  8189.8    29.5  8553.4   30.94
#Mann= 5 , 1 , 0
  3605.2      .2       0  3661.3      .1       0  4970.6    .015       0
  5028.3      .1       0  6007.2      .2       0
#XS Ineff= 2 , 0
       0  4959.3    29.2  5039.4       0    29.5
Permanent Ineff=
       F       F
Bank Sta=4970.6,5028.3
XS Rating Curve= 0 ,0
Exp/Cntr=0.5,0.3

Type RM Length L Ch R = 3 ,1618.0  ,,,
BEGIN DESCRIPTION:
GALVESTON ROAD
Structure ID: C63-3
END DESCRIPTION:
Bridge Culvert--1,0,-1,-1, 0
Deck Dist Width WeirC Skew NumUp NumDn MinLoCord MaxHiCord MaxSubmerge Is_Ogee
10,66,2.6,0, 60, 60, , , 0.95, 0, 1,1,,
  3605.2  3617.3  4310.2  4330.2  4370.2  4375.2  4385.2  4445.2  4575.2  4625.2
  4655.2  4670.6  4757.9  4819.4  4877.9 4896.29  4896.4    4953  4969.1 4969.21
  4969.3 5029.29  5029.4  5094.8  5101.6 5101.71  5161.1  5175.7  5229.8  5299.8
  5329.8  5379.8  5478.4  5864.8  6059.8  6079.8  6129.8  6303.4  6624.8  6684.8
  6704.8  6714.8  6779.7  6934.8  6954.8  7069.8  7109.8  7439.8  7669.8  7804.8
  7829.8  7849.8  7864.8  8169.8  8189.8  8294.8  8394.8  8409.8  8449.8  8553.4
      29   30.65   29.98   29.96   29.91   29.91   29.89   29.82   29.67   29.61
   29.57   29.56   29.52   29.36   29.21   29.24   30.24   30.32   30.39   30.39
   30.39   30.49   30.49   30.48   30.49    29.7   29.59   29.61   29.68    29.7
   29.71   29.75    30.1   30.46    30.3   30.28   30.24   30.08   30.16   30.18
   30.18   30.18    30.2   30.26   30.27   30.32   30.34   30.48   30.57   30.63
   30.64   30.65   30.65   30.78   30.79   30.83   30.87   30.88   31.01   30.94
      29   28.95    28.6      28    28.5    28.7    29.4    29.5    28.5    29.2
    28.3   28.93   28.54   28.49   27.83   27.65   27.65   27.09   25.87   25.87
   26.29   26.39   25.77   29.76   29.69   29.69   29.08   28.54   29.48    28.3
    28.7    27.8   28.21    29.8    29.7    29.3    29.4   29.32    29.5    29.2
    29.2    29.3    29.5    29.9      29    29.9    28.9    30.1    29.7    30.3
    29.9    30.1    29.7    29.6    29.5    30.3    30.4    30.1      31   30.94
  3605.2  3617.3  4310.2  4330.2  4370.2  4375.2  4385.2  4445.2  4575.2  4625.2
  4655.2  4670.6  4757.9  4819.4  4877.9 4896.29  4896.4    4953  4969.1 4969.21
  4969.3 5029.29  5029.4  5094.8  5101.6 5101.71  5161.1  5175.7  5229.8  5299.8
  5329.8  5379.8  5478.4  5864.8  6059.8  6079.8  6129.8  6303.4  6624.8  6684.8
  6704.8  6714.8  6779.7  6934.8  6954.8  7069.8  7109.8  7439.8  7669.8  7804.8
  7829.8  7849.8  7864.8  8169.8  8189.8  8294.8  8394.8  8409.8  8449.8  8553.4
      29   30.65   29.98   29.96   29.91   29.91   29.89   29.82   29.67   29.61
   29.57   29.56   29.52   29.36   29.21   29.24   30.24   30.32   30.39   30.39
   30.39   30.49   30.49   30.48   30.49    29.7   29.59   29.61   29.68    29.7
   29.71   29.75    30.1   30.46    30.3   30.28   30.24   30.08   30.16   30.18
   30.18   30.18    30.2   30.26   30.27   30.32   30.34   30.48   30.57   30.63
   30.64   30.65   30.65   30.78   30.79   30.83   30.87   30.88   31.01   30.94
   28.96   28.91   28.56   27.96   28.46   28.66   29.36   29.46   28.46   29.16
   28.26   28.89    28.5   28.45   27.79   27.61   27.61   27.05   25.83   25.83
   26.25   26.35   25.73   29.72   29.65   29.65   29.04    28.5   29.44   28.26
   28.66   27.76   28.17   29.76   29.66   29.26   29.36   29.28   29.46   29.16
   29.16   29.26   29.46   29.86   28.96   29.86   28.86   30.06   29.66   30.26
   29.86   30.06   29.66   29.56   29.46   30.26   30.36   30.06   30.96    30.9
Abutment Skew #Up #Dn= , 2 , 2
  4969.1  4990.4
   26.29   14.81
  4969.1  4990.4
   26.25   14.77
Abutment Skew #Up #Dn= , 2 , 2
  5008.7 5029.49
   15.04   26.39
  5008.7 5029.49
      15   26.35
BR Coef= 1 , 1 , 0 ,1.25, 0 ,,,0.8,0,2,0,
WSPro=,,,, 1 ,,,, 0 ,,,, 0 ,,,,-1 ,-1 ,-1 , 0 , 0 , 0 , 0 , 0
BR U #Sta/Elev= 93
  3605.2      29  3617.3   28.95  3630.2    28.9  3661.3   28.89  4236.4   28.63
  4310.2    28.6  4330.2      28  4370.2    28.5  4375.2    28.7  4385.2    29.4
  4445.2    29.5  4575.2    28.5  4625.2    29.2  4655.2    28.3  4667.7   28.81
  4670.6   28.93  4757.9   28.54  4758.4   28.54  4819.4   28.49  4875.6   27.85
  4877.9   27.83 4896.29   27.65  4896.4   27.65 4896.51   27.64    4953   27.09
  4959.7   26.58  4969.1   25.87 4969.21   25.87  4969.3   25.86  4970.6   25.76
  4983.8   19.64  4990.3   14.88  4990.4   14.81  4991.9    14.4  4994.5   13.98
    5000   13.94  5000.2   13.94  5006.4   14.29  5008.1   14.58  5008.6   15.01
  5008.7   15.04  5019.8   18.49  5022.7   19.39  5028.3    25.7 5029.29   25.76
  5029.4   25.77  5084.5   29.13  5094.8   29.76 5101.49   29.69  5101.6   29.69
 5101.71   29.69  5161.1   29.08  5175.7   28.54  5216.1   29.24  5229.8   29.48
  5278.8    28.6  5299.8    28.3  5329.8    28.7  5371.6   27.95  5379.8    27.8
  5478.4   28.21  5864.8    29.8  5873.4    29.8  6007.2   29.73  6059.8    29.7
  6079.8    29.3  6129.8    29.4  6183.4   29.36  6264.8    29.3  6303.4   29.32
  6624.8    29.5  6684.8    29.2  6704.8    29.2  6714.8    29.3  6779.7    29.5
  6779.8    29.5  6934.8    29.9  6954.8      29  7069.8    29.9  7109.8    28.9
  7439.8    30.1  7669.8    29.7  7804.8    30.3  7829.8    29.9  7849.8    30.1
  7864.8    29.7  8169.8    29.6  8189.8    29.5  8294.8    30.3  8394.8    30.4
  8409.8    30.1  8449.8      31  8553.4   30.94
BR U #Mann= 5
  3605.2      .2  3661.3      .1  4970.6    .015  5028.3      .1  6007.2      .2
BR U Banks=4970.6,5028.3
BR D #Sta/Elev= 93
  3605.2   28.96  3617.3   28.91  3630.2   28.86  3661.3   28.85  4236.4   28.59
  4310.2   28.56  4330.2   27.96  4370.2   28.46  4375.2   28.66  4385.2   29.36
  4445.2   29.46  4575.2   28.46  4625.2   29.16  4655.2   28.26  4667.7   28.77
  4670.6   28.89  4757.9    28.5  4758.4    28.5  4819.4   28.45  4875.6   27.81
  4877.9   27.79 4896.29   27.61  4896.4   27.61 4896.51    27.6    4953   27.05
  4959.7   26.54  4969.1   25.83 4969.21   25.83  4969.3   25.82  4970.6   25.72
  4983.8    19.6  4990.3   14.84  4990.4   14.77  4991.9   14.36  4994.5   13.94
    5000    13.9  5000.2    13.9  5006.4   14.25  5008.1   14.54  5008.6   14.97
  5008.7      15  5019.8   18.45  5022.7   19.35  5028.3   25.66 5029.29   25.72
  5029.4   25.73  5084.5   29.09  5094.8   29.72 5101.49   29.65  5101.6   29.65
 5101.71   29.65  5161.1   29.04  5175.7    28.5  5216.1    29.2  5229.8   29.44
  5278.8   28.56  5299.8   28.26  5329.8   28.66  5371.6   27.91  5379.8   27.76
  5478.4   28.17  5864.8   29.76  5873.4   29.76  6007.2   29.69  6059.8   29.66
  6079.8   29.26  6129.8   29.36  6183.4   29.32  6264.8   29.26  6303.4   29.28
  6624.8   29.46  6684.8   29.16  6704.8   29.16  6714.8   29.26  6779.7   29.46
  6779.8   29.46  6934.8   29.86  6954.8   28.96  7069.8   29.86  7109.8   28.86
  7439.8   30.06  7669.8   29.66  7804.8   30.26  7829.8   29.86  7849.8   30.06
  7864.8   29.66  8169.8   29.56  8189.8   29.46  8294.8   30.26  8394.8   30.36
  8409.8   30.06  8449.8   30.96  8553.4    30.9
BR D #Mann= 5
  3605.2      .2  3661.3      .1  4970.6    .015  5028.3      .1  6007.2      .2
BR D Banks=4970.6,5028.3
BC Design=,, 0 ,, 0 ,,,,,,
BC HTab HWMax=31
BC Use User HTab Curves=0
BC User HTab FreeFlow(D)= 0

Type RM Length L Ch R = 1 ,1575.0  ,11.5,11.5,11.5
BEGIN DESCRIPTION:
Downstream Section of Bridge/Culvert/Weir
END DESCRIPTION:
XS GIS Cut Line= 6
      3160519.15      13811628.9      3161073.11     13811029.22
      3161442.99     13810622.15      3161463.29     13810601.71
       3161476.7     13810587.07      3163779.34     13807907.35
#Sta/Elev= 30
  3605.2   29.31  3661.3    29.2  4330.2   28.31  4385.2   29.71  4575.2   28.81
  4625.2   29.51  4655.2   28.61  4670.6   29.24  4819.4    28.8    4953    27.4
  4970.6   26.07  4983.8   19.95  4990.4   15.12    5000   14.25  5008.1   14.89
  5022.7    19.7  5028.3   26.01  5094.8   30.07  5175.7   28.85  5229.8   29.79
  5379.8   28.11  6007.2   30.04  6704.8   29.51  6934.8   30.21  6954.8   29.31
  7069.8   30.21  7109.8   29.21  7439.8   30.41  8189.8   29.81  8553.4   31.25
#Mann= 5 , 1 , 0
  3605.2      .2       0  3661.3      .1       0  4970.6    .015       0
  5028.3      .1       0  6007.2      .2       0
#XS Ineff= 2 , 0
       0  4959.3      29  5039.4       0    29.3
Permanent Ineff=
       F       F
Bank Sta=4970.6,5028.3
XS Rating Curve= 0 ,0
Exp/Cntr=0.5,0.3

Type RM Length L Ch R = 3 ,1574.0  ,,,
BEGIN DESCRIPTION:
PIPELINE D/S OF GALVESTON ROAD
END DESCRIPTION:
Bridge Culvert--1,0,-1,-1, 0
Deck Dist Width WeirC Skew NumUp NumDn MinLoCord MaxHiCord MaxSubmerge Is_Ogee
10,1,2.6,0, 56, 56, , , 0.95, 0, 1,1,,
  3605.2  3630.2  4310.2  4330.2  4370.2  4375.2  4385.2  4445.2  4575.2  4625.2
  4655.2  4780.2 4843.17 4897.77 4949.47 4950.37 4952.67 5036.87 5038.26 5038.37
 5038.47 5066.87 5129.97 5130.37  5141.8  5146.8  5241.8  5299.8  5329.8  5379.8
  5864.8  6059.8  6079.8  6129.8  6264.8  6624.8  6684.8  6704.8  6714.8  6779.8
  6934.8  6954.8  7069.8  7109.8  7439.8  7669.8  7804.8  7829.8  7849.8  7864.8
  8169.8  8189.8  8294.8  8394.8  8409.8  8449.8
      29    28.9    28.6      28    28.5    28.7    29.4    29.5    28.5    29.2
    28.3    28.4   27.76   27.56   26.75   26.75   27.95   27.85   26.51    26.4
   25.93   27.42    27.8   27.67    28.1    28.5    29.4    28.3    28.7    27.8
    29.8    29.7    29.3    29.4    29.3    29.5    29.2    29.2    29.3    29.5
    29.9      29    29.9    28.9    30.1    29.7    30.3    29.9    30.1    29.7
    29.6    29.5    30.3    30.4    30.1      31
      29    28.9    28.6      28    28.5    28.7    29.4    29.5    28.5    29.2
    28.3    28.4   27.76   27.56   26.75   26.67   26.95   26.85   25.92   25.92
   25.93   27.42    27.8   27.67    28.1    28.5    29.4    28.3    28.7    27.8
    29.8    29.7    29.3    29.4    29.3    29.5    29.2    29.2    29.3    29.5
    29.9      29    29.9    28.9    30.1    29.7    30.3    29.9    30.1    29.7
    29.6    29.5    30.3    30.4    30.1      31
  3605.2  3630.2  4310.2  4330.2  4370.2  4375.2  4385.2  4445.2  4575.2  4625.2
  4655.2  4780.2 4843.17 4897.77 4949.47 4950.37 4952.67 5036.87 5038.26 5038.37
 5038.47 5066.87 5129.97 5130.37  5141.8  5146.8  5241.8  5299.8  5329.8  5379.8
  5864.8  6059.8  6079.8  6129.8  6264.8  6624.8  6684.8  6704.8  6714.8  6779.8
  6934.8  6954.8  7069.8  7109.8  7439.8  7669.8  7804.8  7829.8  7849.8  7864.8
  8169.8  8189.8  8294.8  8394.8  8409.8  8449.8
      29    28.9    28.6      28    28.5    28.7    29.4    29.5    28.5    29.2
    28.3    28.4   27.76   27.56   26.75   26.75   27.95   27.85   26.51    26.4
   25.93   27.42    27.8   27.67    28.1    28.5    29.4    28.3    28.7    27.8
    29.8    29.7    29.3    29.4    29.3    29.5    29.2    29.2    29.3    29.5
    29.9      29    29.9    28.9    30.1    29.7    30.3    29.9    30.1    29.7
    29.6    29.5    30.3    30.4    30.1      31
      29    28.9    28.6      28    28.5    28.7    29.4    29.5    28.5    29.2
    28.3    28.4   27.76   27.56   26.75   26.67   26.95   26.85   25.92   25.92
   25.93   27.42    27.8   27.67    28.1    28.5    29.4    28.3    28.7    27.8
    29.8    29.7    29.3    29.4    29.3    29.5    29.2    29.2    29.3    29.5
    29.9      29    29.9    28.9    30.1    29.7    30.3    29.9    30.1    29.7
    29.6    29.5    30.3    30.4    30.1      31
Pier Skew, UpSta & Num, DnSta & Num=  ,4985.8, 2 ,4985.8, 2 , 0 , 0 , 0 ,,
     1.3     1.3
   16.22   27.91
     1.3     1.3
   16.22   27.91
Pier Skew, UpSta & Num, DnSta & Num=  ,5015.2, 2 ,5015.2, 2 , 0 , 0 , 0 ,,
     1.3     1.3
   16.64   27.87
     1.3     1.3
   16.64   27.87
BR Coef= 1 , 1 , 0 ,1.25, 0 ,,,0.8,0,2,0,
WSPro=,,,, 1 ,,,, 0 ,,,, 0 ,,,,-1 ,-1 ,-1 , 0 , 0 , 0 , 0 , 0
BR U #Sta/Elev= 69
  3605.2      29  3630.2    28.9  3661.3   28.89  4310.2    28.6  4330.2      28
  4370.2    28.5  4375.2    28.7  4385.2    29.4  4445.2    29.5  4575.2    28.5
  4625.2    29.2  4655.2    28.3  4780.2    28.4  4785.2    28.3 4843.17   27.76
 4897.77   27.56 4949.47   26.75 4950.37   26.67 4950.48   26.67 4950.57   26.66
 4952.67   26.48 4970.17   25.01 4992.27   14.42 4994.87    14.3 4999.57   14.27
 5007.67   14.56 5007.77   14.38 5030.87   25.53 5036.87   25.85 5038.26   25.92
 5038.37   25.92 5038.47   25.93 5066.87   27.42 5129.97    27.8 5130.37   27.67
  5141.8    28.1  5146.8    28.5  5241.8    29.4  5244.8    29.3  5299.8    28.3
  5329.8    28.7  5379.8    27.8  5864.8    29.8  6007.2   29.73  6059.8    29.7
  6079.8    29.3  6129.8    29.4  6264.8    29.3  6624.8    29.5  6684.8    29.2
  6704.8    29.2  6714.8    29.3  6779.8    29.5  6934.8    29.9  6954.8      29
  7069.8    29.9  7109.8    28.9  7439.8    30.1  7669.8    29.7  7804.8    30.3
  7829.8    29.9  7849.8    30.1  7864.8    29.7  8169.8    29.6  8189.8    29.5
  8294.8    30.3  8394.8    30.4  8409.8    30.1  8449.8      31
BR U #Mann= 5
  3605.2      .2  3661.3      .1 4970.17    .015 5030.87      .1  6007.2      .2
BR U Banks=4970.17,5030.87
BR D #Sta/Elev= 69
  3605.2      29  3630.2    28.9  3661.3   28.89  4310.2    28.6  4330.2      28
  4370.2    28.5  4375.2    28.7  4385.2    29.4  4445.2    29.5  4575.2    28.5
  4625.2    29.2  4655.2    28.3  4780.2    28.4  4785.2    28.3 4843.17   27.76
 4897.77   27.56 4949.47   26.75 4950.37   26.67 4950.48   26.67 4950.57   26.66
 4952.67   26.48 4970.17   25.01 4992.27   14.42 4994.87    14.3 4999.57   14.27
 5007.67   14.56 5007.77   14.38 5030.87   25.53 5036.87   25.85 5038.26   25.92
 5038.37   25.92 5038.47   25.93 5066.87   27.42 5129.97    27.8 5130.37   27.67
  5141.8    28.1  5146.8    28.5  5241.8    29.4  5244.8    29.3  5299.8    28.3
  5329.8    28.7  5379.8    27.8  5864.8    29.8  6007.2   29.73  6059.8    29.7
  6079.8    29.3  6129.8    29.4  6264.8    29.3  6624.8    29.5  6684.8    29.2
  6704.8    29.2  6714.8    29.3  6779.8    29.5  6934.8    29.9  6954.8      29
  7069.8    29.9  7109.8    28.9  7439.8    30.1  7669.8    29.7  7804.8    30.3
  7829.8    29.9  7849.8    30.1  7864.8    29.7  8169.8    29.6  8189.8    29.5
  8294.8    30.3  8394.8    30.4  8409.8    30.1  8449.8      31
BR D #Mann= 5
  3605.2      .2  3661.3      .1 4970.17    .015 5030.87      .1  6007.2      .2
BR D Banks=4970.17,5030.87
BC Design=,, 0 ,, 0 ,,,,,,
BC HTab HWMax=31.31
BC Use User HTab Curves=0
BC User HTab FreeFlow(D)= 0

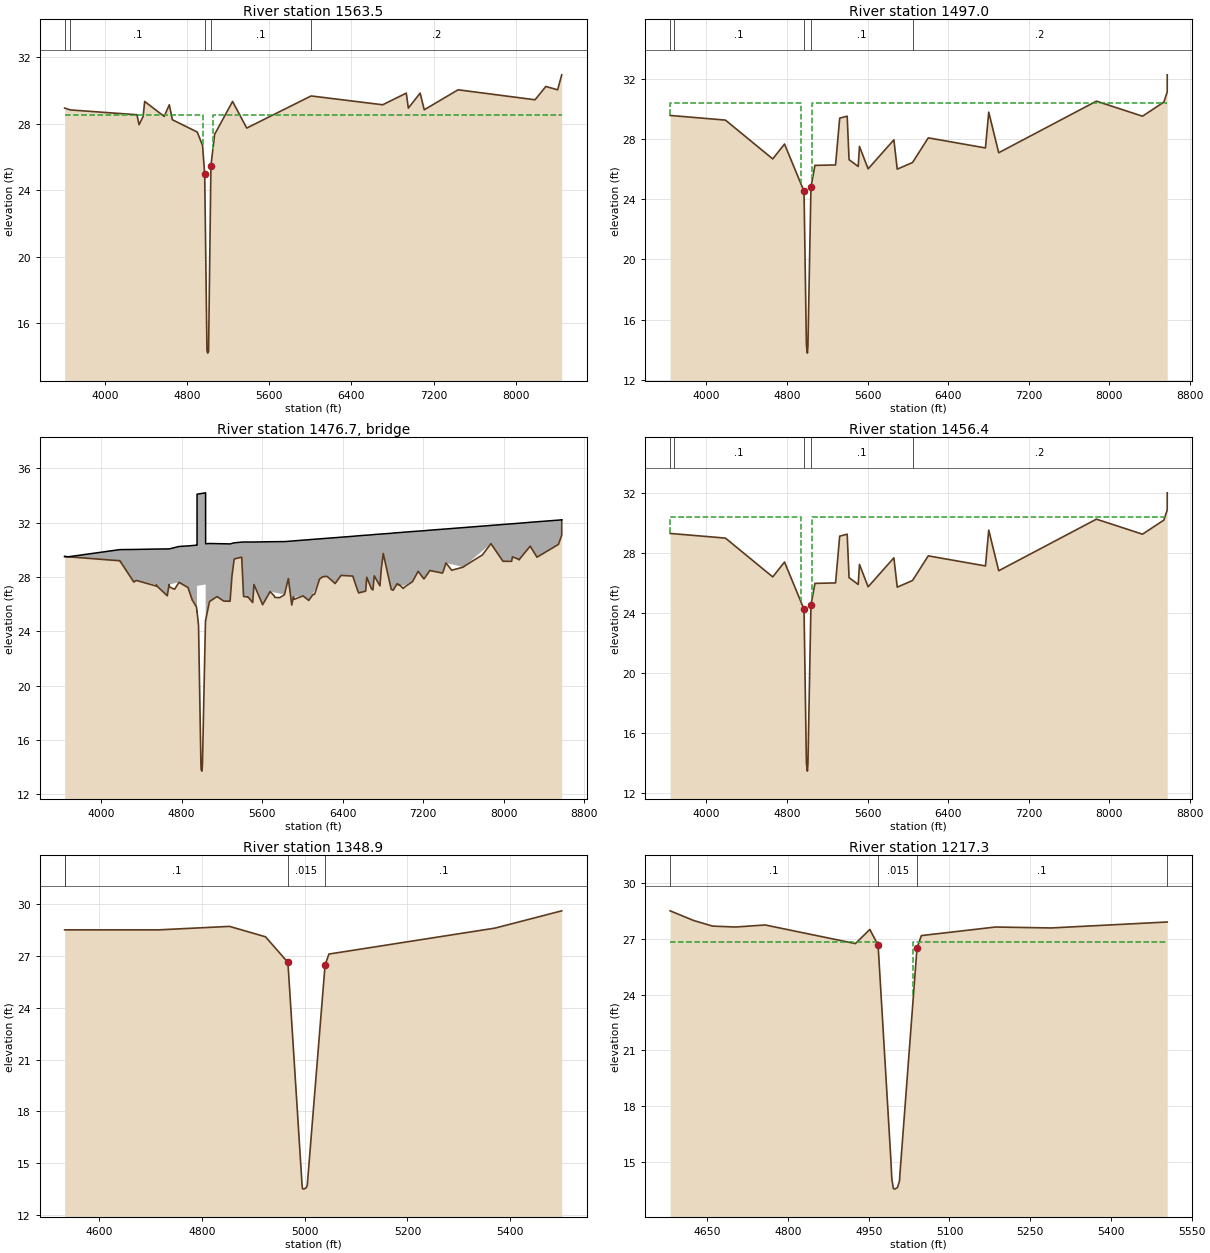
Type RM Length L Ch R = 1 ,1563.5  ,66.5,66.5,66.5
BEGIN DESCRIPTION:
Downstream Section of Bridge/Culvert/Weir
END DESCRIPTION:
XS GIS Cut Line= 6
      3160567.35     13811690.07      3161064.17     13811120.08
      3161455.61     13810680.69      3161515.91     13810618.37
       3162749.6     13809103.09      3163709.83     13808004.21
#Sta/Elev= 30
  3605.2   28.93  3661.3   28.82  4310.2   28.53  4330.2   27.93  4370.2   28.43
  4385.2   29.33  4575.2   28.43  4625.2   29.13  4655.2   28.23 4897.77   27.49
 4949.47   26.68 4970.17   24.94 4992.27   14.35 4999.57    14.2 5007.77   14.31
 5030.87   25.46 5066.87   27.35  5241.8   29.33  5379.8   27.73  6007.2   29.66
  6704.8   29.13  6934.8   29.83  6954.8   28.93  7069.8   29.83  7109.8   28.83
  7439.8   30.03  8189.8   29.43  8294.8   30.23  8409.8   30.03  8449.8   30.93
#Mann= 5 , 1 , 0
  3605.2      .2       0  3661.3      .1       0 4970.17    .015       0
 5030.87      .1       0  6007.2      .2       0
#XS Ineff= 2 , 0
       0  4950.3    28.5  5049.4       0    28.5
Permanent Ineff=
       F       F
Bank Sta=4970.17,5030.87
XS Rating Curve= 0 ,0
Exp/Cntr=0.5,0.3

Type RM Length L Ch R = 1 ,1497.0  ,40.6,40.6,40.6
BEGIN DESCRIPTION:
Upstream Section of Bridge/Culvert/Weir
END DESCRIPTION:
XS GIS Cut Line= 6
      3160624.89     13811708.26      3161085.51     13811162.46
      3161402.13     13810800.47      3161508.97     13810675.47
      3161587.66     13810584.67       3163858.7     13807976.81
#Sta/Elev= 30
  3638.9   29.57  3675.3   29.55  4188.3   29.26  4658.2   26.68  4775.2   27.67
  4968.8   24.53  4992.5    14.3  5002.4   13.77  5007.7   14.26  5037.8   24.81
  5077.4   26.25  5282.2   26.28  5323.2   29.39  5397.5   29.52  5416.3   26.63
  5507.1   26.18  5519.6   27.51  5605.7   26.02  5861.4   27.95  5894.8      26
  6046.6   26.44    6203   28.08  6771.1   27.41  6803.7   29.79  6902.8   27.09
  7873.3   30.52    8331   29.52  8543.7   30.46  8576.6   31.13  8576.7   32.27
#Mann= 5 , 1 , 0
  3638.9      .2       0  3675.3      .1       0  4968.8    .015       0
  5037.8      .1       0  6046.6      .2       0
#XS Ineff= 2 , 0
       0    4943    30.4    5050       0    30.4
Permanent Ineff=
       F       F
Bank Sta=4968.8,5037.8
XS Rating Curve= 0 ,0
Exp/Cntr=0.5,0.3

Type RM Length L Ch R = 3 ,1476.7  ,,,
BEGIN DESCRIPTION:
UNION PACIFIC RAILROAD
Structure ID: C63-2
END DESCRIPTION:
Bridge Culvert--1,0,-1,-1, 0
Deck Dist Width WeirC Skew NumUp NumDn MinLoCord MaxHiCord MaxSubmerge Is_Ogee
10,20.6,2.6,0, 60, 60, , , 0.95, 0, 1,1,,
  3638.9  3675.3  4188.3  4326.2  4549.5  4658.2  4676.9  4775.2  4863.9  4953.5
 4953.61  4953.7 4953.99  4954.1  5037.8  5039.2 5039.31 5039.69  5039.8  5077.4
  5282.2  5323.2  5397.5  5416.3  5507.1  5519.6  5605.7    5680  5822.5  5861.4
  5894.8  5911.6  6064.3    6203    6326  6501.3  6560.3  6629.1  6639.8  6700.9
  6714.3  6771.1  6803.7    6883  6902.8  7093.1  7150.5  7207.8  7267.5  7391.4
    7427  7597.9  7873.3  7992.9  8151.4  8263.5    8331  8543.7  8576.6  8576.7
    29.5   29.48   30.01   30.02   30.05   30.06   30.06   30.24   30.28   30.34
   30.34   30.34   30.34   34.09   34.19   34.19   30.44   30.44   30.44   30.46
   30.43   30.51   30.56   30.57   30.57   30.57   30.58   30.59    30.6   30.62
   30.64   30.65   30.74   30.82   30.89   30.99   31.03   31.07   31.07   31.11
   31.12   31.15   31.17   31.21   31.23   31.34   31.37    31.4   31.44   31.51
   31.53   31.63   31.79   31.86   31.95   32.02   32.06   32.18    32.2    32.2
    29.5   29.48   29.19   27.62   27.42   26.61   27.44    27.6   27.22   25.46
   25.46   27.34   27.34   27.34   27.44   27.44   27.44   27.44   24.81   26.18
   26.21   29.32   29.45   26.56   26.11   27.44   25.95   26.92   26.69   27.88
   25.93   26.53   26.27   28.01   27.51   28.06   26.82   26.95   27.97   27.04
   28.08   27.34   29.72   27.08   27.02   27.64   28.41   27.85   28.47   28.28
   29.03   28.72   30.45   29.15   29.25   30.26   29.45   30.39   31.06    32.2
  3638.9  3675.3  4188.3  4326.2  4549.5  4658.2  4676.9  4775.2  4863.9  4953.5
 4953.61  4953.7 4953.99  4954.1  5037.8  5039.2 5039.31 5039.69  5039.8  5077.4
  5282.2  5323.2  5397.5  5416.3  5507.1  5519.6  5605.7    5680  5822.5  5861.4
  5894.8  5911.6  6064.3    6203    6326  6501.3  6560.3  6629.1  6639.8  6700.9
  6714.3  6771.1  6803.7    6883  6902.8  7093.1  7150.5  7207.8  7267.5  7391.4
    7427  7597.9  7873.3  7992.9  8151.4  8263.5    8331  8543.7  8576.6  8576.7
    29.5   29.48   30.01   30.02   30.05   30.06   30.06   30.24   30.28   30.34
   30.34   30.34   30.34   34.09   34.19   34.19   30.44   30.44   30.44   30.46
   30.43   30.51   30.56   30.57   30.57   30.57   30.58   30.59    30.6   30.62
   30.64   30.65   30.74   30.82   30.89   30.99   31.03   31.07   31.07   31.11
   31.12   31.15   31.17   31.21   31.23   31.34   31.37    31.4   31.44   31.51
   31.53   31.63   31.79   31.86   31.95   32.02   32.06   32.18    32.2    32.2
   29.28   29.26   28.97    27.4    27.2   26.39   27.22   27.38      27   25.24
   25.24   27.12   27.12   27.12   27.22   27.22   27.22   27.22   24.59   25.96
   25.99    29.1   29.23   26.34   25.89   27.22   25.73    26.7   26.47   27.66
   25.71   26.31   26.05   27.79   27.29   27.84    26.6   26.73   27.75   26.82
   27.86   27.12    29.5   26.86    26.8   27.42   28.19   27.63   28.25   28.06
   28.81    28.5   30.23   28.93   29.03   30.04   29.23   30.17   30.84   31.98
Abutment Skew #Up #Dn= , 2 , 2
  4953.5  4992.5
   27.34   14.23
  4953.5  4992.5
   27.12   14.01
Abutment Skew #Up #Dn= , 2 , 2
  5007.7 5039.89
   14.19   27.44
  5007.7 5039.89
   13.97   27.22
BR Coef= 1 , 1 , 0 ,1.25, 0 ,,,0.8,0,2,0,
WSPro=,,,, 1 ,,,, 0 ,,,, 0 ,,,,-1 ,-1 ,-1 , 0 , 0 , 0 , 0 , 0
BR U #Sta/Elev= 127
  3638.9    29.5  3675.3   29.48  4128.4   29.22  4188.3   29.19  4188.8   29.17
  4326.2   27.62    4350   27.74  4547.8   27.33  4549.5   27.42    4551   27.36
  4658.2   26.61  4676.9   27.44  4680.3   27.26  4728.1    27.1  4730.9   27.09
  4775.2    27.6  4800.9   27.49  4863.9   27.22  4864.4   27.21  4905.9   26.31
  4908.3   26.28  4948.7   25.78  4953.5   25.46 4953.61   25.46  4953.7   25.45
 4953.99   25.43  4954.1   25.43 4954.21   25.42  4968.8   24.46  4992.4   14.27
  4992.5   14.23  4993.6   14.04  4995.2    13.8  4998.5   13.75  5002.4    13.7
  5006.4   14.04  5007.6   14.18  5007.7   14.19  5037.8   24.74 5039.09   24.79
  5039.2   24.79 5039.31   24.79 5039.69   24.81  5039.8   24.81  5039.9   24.82
  5077.4   26.18  5115.5   26.37  5153.2   26.55  5186.8   26.38    5219   26.22
  5266.7   26.21  5282.2   26.21  5300.9   28.06  5323.2   29.32  5345.5   29.36
  5397.5   29.45  5416.3   26.56  5453.9   26.52  5457.3   26.54  5507.1   26.11
  5519.6   27.44  5578.2   26.43  5605.7   25.95    5680   26.92  5719.9   26.61
  5726.2   26.49  5774.4   26.47  5822.5   26.69  5828.4   26.87  5861.4   27.88
  5894.8   25.93  5911.6   26.53  5918.9   26.35  6007.4    26.6  6046.6   26.37
  6064.3   26.27  6103.3   26.68  6122.4   26.73    6171   27.84    6203   28.01
  6245.7   28.04  6315.5   27.58    6326   27.51  6384.2   28.11  6501.3   28.06
  6549.8   26.99  6560.3   26.82  6629.1   26.95  6639.8   27.97  6686.5   27.13
  6700.9   27.04  6714.3   28.08  6771.1   27.34  6784.1   28.57  6803.7   29.72
    6883   27.08  6902.8   27.02  6942.4   27.51  6955.4    27.4  6962.3   27.44
  7001.9   27.15  7021.7   27.29  7093.1   27.64    7101   27.74  7150.5   28.41
  7207.8   27.85  7219.9   27.97  7267.5   28.47  7391.4   28.28  7398.3   28.38
    7427   29.03  7483.2   28.49  7597.9   28.72  7616.3   28.82  7671.6   29.08
  7788.6   29.62  7873.3   30.45  7992.9   29.15  8079.9   29.15  8086.4   29.48
  8150.2   29.29  8151.4   29.25  8263.5   30.26    8331   29.45  8543.7   30.39
  8576.6   31.06  8576.7    32.2
BR U #Mann= 5
  3638.9      .2  3675.3      .1  4968.8    .015  5037.8      .1  6046.6      .2
BR U Banks=4968.8,5037.8
BR D #Sta/Elev= 127
  3638.9   29.28  3675.3   29.26  4128.4      29  4188.3   28.97  4188.8   28.95
  4326.2    27.4    4350   27.52  4547.8   27.11  4549.5    27.2    4551   27.14
  4658.2   26.39  4676.9   27.22  4680.3   27.04  4728.1   26.88  4730.9   26.87
  4775.2   27.38  4800.9   27.27  4863.9      27  4864.4   26.99  4905.9   26.09
  4908.3   26.06  4948.7   25.56  4953.5   25.24 4953.61   25.24  4953.7   25.23
 4953.99   25.21  4954.1   25.21 4954.21    25.2  4968.8   24.24  4992.4   14.05
  4992.5   14.01  4993.6   13.82  4995.2   13.58  4998.5   13.53  5002.4   13.48
  5006.4   13.82  5007.6   13.96  5007.7   13.97  5037.8   24.52 5039.09   24.57
  5039.2   24.57 5039.31   24.57 5039.69   24.59  5039.8   24.59  5039.9    24.6
  5077.4   25.96  5115.5   26.15  5153.2   26.33  5186.8   26.16    5219      26
  5266.7   25.99  5282.2   25.99  5300.9   27.84  5323.2    29.1  5345.5   29.14
  5397.5   29.23  5416.3   26.34  5453.9    26.3  5457.3   26.32  5507.1   25.89
  5519.6   27.22  5578.2   26.21  5605.7   25.73    5680    26.7  5719.9   26.39
  5726.2   26.27  5774.4   26.25  5822.5   26.47  5828.4   26.65  5861.4   27.66
  5894.8   25.71  5911.6   26.31  5918.9   26.13  6007.4   26.38  6046.6   26.15
  6064.3   26.05  6103.3   26.46  6122.4   26.51    6171   27.62    6203   27.79
  6245.7   27.82  6315.5   27.36    6326   27.29  6384.2   27.89  6501.3   27.84
  6549.8   26.77  6560.3    26.6  6629.1   26.73  6639.8   27.75  6686.5   26.91
  6700.9   26.82  6714.3   27.86  6771.1   27.12  6784.1   28.35  6803.7    29.5
    6883   26.86  6902.8    26.8  6942.4   27.29  6955.4   27.18  6962.3   27.22
  7001.9   26.93  7021.7   27.07  7093.1   27.42    7101   27.52  7150.5   28.19
  7207.8   27.63  7219.9   27.75  7267.5   28.25  7391.4   28.06  7398.3   28.16
    7427   28.81  7483.2   28.27  7597.9    28.5  7616.3    28.6  7671.6   28.86
  7788.6    29.4  7873.3   30.23  7992.9   28.93  8079.9   28.93  8086.4   29.26
  8150.2   29.07  8151.4   29.03  8263.5   30.04    8331   29.23  8543.7   30.17
  8576.6   30.84  8576.7   31.98
BR D #Mann= 5
  3638.9      .2  3675.3      .1  4968.8    .015  5037.8      .1  6046.6      .2
BR D Banks=4968.8,5037.8
BC Design=,, 0 ,, 0 ,,,,,,
BC HTab HWMax=32.27
BC Use User HTab Curves=0
BC User HTab FreeFlow(D)= 0

Type RM Length L Ch R = 1 ,1456.4  ,107.5,107.5,107.5
BEGIN DESCRIPTION:
Downstream Section of Bridge/Culvert/Weir
END DESCRIPTION:
XS GIS Cut Line= 6
       3160646.7     13811742.51      3161107.33      13811196.7
      3161423.95     13810834.71      3161530.79     13810709.71
      3161609.48     13810618.91      3163880.52     13808011.05
#Sta/Elev= 30
  3638.9   29.28  3675.3   29.26  4188.3   28.97  4658.2   26.39  4775.2   27.38
  4968.8   24.24  4992.5   14.01  5002.4   13.48  5007.7   13.97  5037.8   24.52
  5077.4   25.96  5282.2   25.99  5323.2    29.1  5397.5   29.23  5416.3   26.34
  5507.1   25.89  5519.6   27.22  5605.7   25.73  5861.4   27.66  5894.8   25.71
  6046.6   26.15    6203   27.79  6771.1   27.12  6803.7    29.5  6902.8    26.8
  7873.3   30.23    8331   29.23  8543.7   30.17  8576.6   30.84  8576.7   31.98
#Mann= 5 , 1 , 0
  3638.9      .2       0  3675.3      .1       0  4968.8    .015       0
  5037.8      .1       0  6046.6      .2       0
#XS Ineff= 2 , 0
       0    4943    30.4    5050       0    30.4
Permanent Ineff=
       F       F
Bank Sta=4968.8,5037.8
XS Rating Curve= 0 ,0
Exp/Cntr=0.5,0.3

Type RM Length L Ch R = 1 ,1348.9  ,130,131.6,144.6
BEGIN DESCRIPTION:
Cross Section 1348.9-Interpolated
END DESCRIPTION:
XS GIS Cut Line= 6
      3161268.48     13811139.43      3161404.15     13811016.29
       3161493.9     13810911.93      3161552.34     13810838.88
      3161905.07     13810605.11      3161990.59      13810507.2
#Sta/Elev= 14
  4532.8    28.5    4716    28.5  4853.7    28.7  4923.7    28.1  4967.4   26.62
    4995   13.73  4995.8   13.54  4998.3   13.51  5003.5    13.6  5005.1   13.75
  5039.7   26.46  5047.2    27.1  5370.4    28.6  5500.4    29.6
#Mann= 4 , 1 , 0
  4532.8      .2       0  4532.8      .1       0  4967.4    .015       0
  5039.7      .1       0
Bank Sta=4967.4,5039.7
XS Rating Curve= 0 ,0
Exp/Cntr=0.5,0.3

Type RM Length L Ch R = 1 ,1217.3  ,80,80,80
BEGIN DESCRIPTION:
Upstream Section of Bridge/Culvert/Weir
END DESCRIPTION:
XS GIS Cut Line= 6
      3161337.35     13811172.38       3161471.8     13811031.85
      3161670.36     13810921.54      3161864.58     13810844.24
       3162056.4     13810716.36      3162106.23     13810678.81
#Sta/Elev= 20
    4581    28.5  4624.7   27.98  4659.9   27.68  4702.3   27.63  4757.6   27.74
  4925.3   26.74    4952    27.5  4967.4   26.66  4990.8   15.29  4992.9    14.1
  4995.8   13.58  4998.3   13.55  5003.5   13.64  5007.3   14.01  5007.7   14.26
  5039.7    26.5  5047.8   27.17  5185.5   27.63  5288.8   27.58  5504.6    27.9
#Mann= 4 , 1 , 0
    4581      .1       0  4967.4    .015       0  5039.7      .1       0
  5504.6      .2       0
#XS Ineff= 2 , 0
       0    4967    26.8  5033.1       0    26.8
Permanent Ineff=
       F       F
Bank Sta=4967.4,5039.7
XS Rating Curve= 0 ,0
Exp/Cntr=0.5,0.3

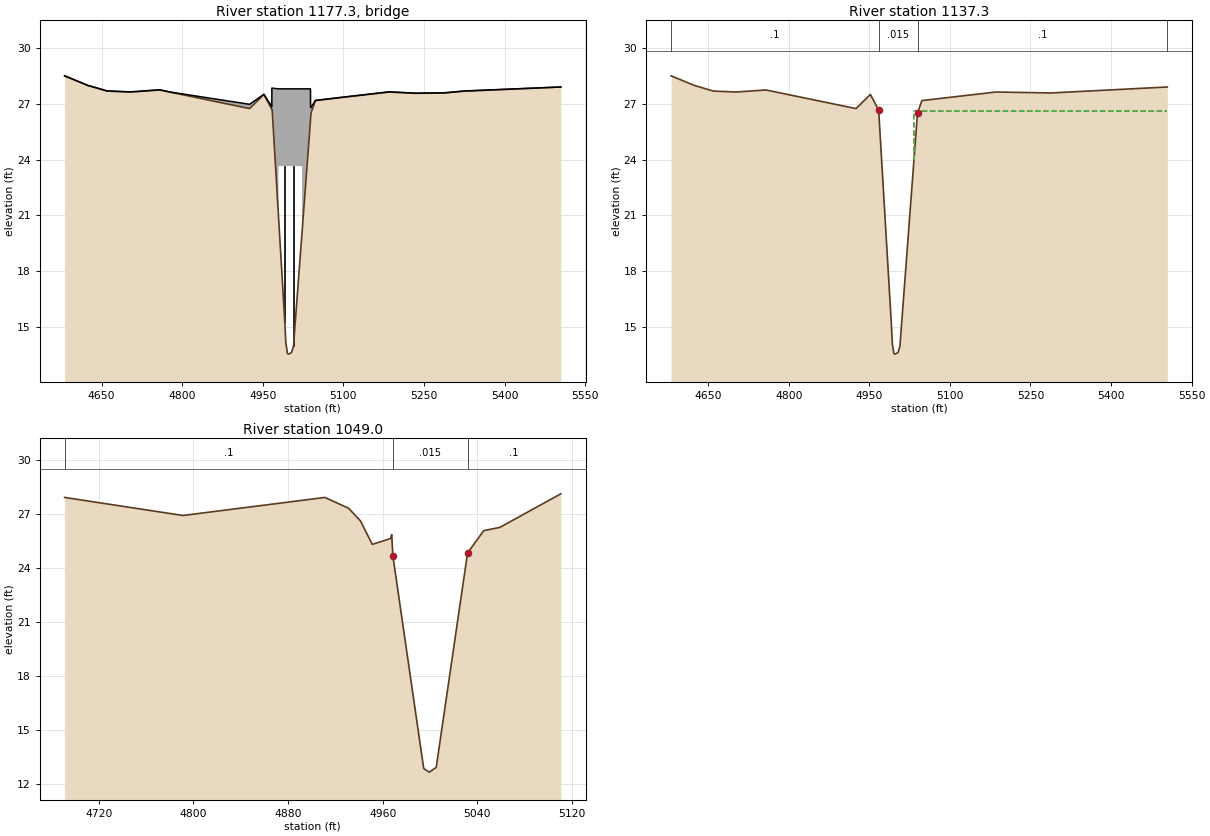
Type RM Length L Ch R = 3 ,1177.3  ,,,
BEGIN DESCRIPTION:
FORREST OAKS BOULEVARD
Structure ID: C63-1
END DESCRIPTION:
Bridge Culvert--1,0,-1,-1, 0
Deck Dist Width WeirC Skew NumUp NumDn MinLoCord MaxHiCord MaxSubmerge Is_Ogee
10,60,2.6,0, 45, 45, , , 0.95, 0, 1,1,,
    4581  4624.7  4643.6  4659.9  4702.3  4714.8  4757.6  4779.7  4925.3    4952
 4966.69  4966.8 4966.91  4967.4  4978.8  4978.9 4979.01  4979.1  4987.1  4990.8
  4992.9    4995  4995.8  4998.3  5003.5  5005.1  5007.3  5007.7  5016.7 5022.99
  5023.1 5038.59  5038.7 5038.81  5039.1  5039.7  5047.8  5109.6  5185.5  5198.3
  5234.8  5288.8  5326.3  5328.1  5504.6
    28.5   27.98   27.83   27.69   27.64   27.66   27.75   27.62   26.97   27.51
   26.84   27.84   27.84   27.84    27.8    27.8    27.8    27.8    27.8    27.8
    27.8    27.8    27.8    27.8    27.8    27.8    27.8    27.8    27.8    27.8
    27.8    27.8    27.8    26.8    26.8    26.8   27.18   27.39   27.64   27.62
   27.57   27.59   27.69   27.69    27.9
    28.5   27.98   27.82   27.68   27.63   27.65   27.74   27.61   26.74    27.5
    26.7   26.69   26.69   26.66   21.12   21.07   21.02   23.65   23.65   23.65
   23.65   23.65   23.65   23.65   23.65   23.65   23.65   23.65   23.65   23.65
   20.15   26.08   26.12   26.16   26.27    26.5   27.17   27.38   27.63   27.61
   27.56   27.58   27.68   27.68    27.9
    4581  4624.7  4643.6  4659.9  4702.3  4714.8  4757.6  4779.7  4925.3    4952
 4966.69  4966.8 4966.91  4967.4  4978.8  4978.9 4979.01  4979.1  4987.1  4990.8
  4992.9    4995  4995.8  4998.3  5003.5  5005.1  5007.3  5007.7  5016.7 5022.99
  5023.1 5038.59  5038.7 5038.81  5039.1  5039.7  5047.8  5109.6  5185.5  5198.3
  5234.8  5288.8  5326.3  5328.1  5504.6
    28.5   27.98   27.83   27.69   27.64   27.66   27.75   27.62   26.97   27.51
   26.84   27.84   27.84   27.84    27.8    27.8    27.8    27.8    27.8    27.8
    27.8    27.8    27.8    27.8    27.8    27.8    27.8    27.8    27.8    27.8
    27.8    27.8    27.8    26.8    26.8    26.8   27.18   27.39   27.64   27.62
   27.57   27.59   27.69   27.69    27.9
   28.25   27.73   27.57   27.43   27.38    27.4   27.49   27.36   26.49   27.25
   26.45   26.44   26.44   26.41   20.87   20.82   20.77    23.4    23.4    23.4
    23.4    23.4    23.4    23.4    23.4    23.4    23.4    23.4    23.4    23.4
    19.9   25.83   25.87   25.91   26.02   26.25   26.92   27.13   27.38   27.36
   27.31   27.33   27.43   27.43   27.65
Pier Skew, UpSta & Num, DnSta & Num=  ,4990.8, 2 ,4990.8, 2 , 0 , 0 , 0 ,,
     1.4     1.4
   13.89   24.65
     1.4     1.4
   13.64    24.4
Pier Skew, UpSta & Num, DnSta & Num=  ,5007.3, 2 ,5007.3, 2 , 0 , 0 , 0 ,,
     1.4     1.4
   12.94   24.65
     1.4     1.4
   12.69    24.4
Abutment Skew #Up #Dn= , 2 , 2
  4978.9  4987.1
   23.65   17.09
  4978.9  4987.1
    23.4   16.84
Abutment Skew #Up #Dn= , 2 , 2
  5016.7 5023.19
    17.7   23.65
  5016.7 5023.19
   17.45    23.4
BR Coef= 1 , 1 , 0 ,1.25, 0 ,,,0.8,0,2,0,
WSPro=,,,, 1 ,,,, 0 ,,,, 0 ,,,,-1 ,-1 ,-1 , 0 , 0 , 0 , 0 , 0
BR U #Sta/Elev= 45
    4581    28.5  4624.7   27.98  4643.6   27.82  4659.9   27.68  4702.3   27.63
  4714.8   27.65  4757.6   27.74  4779.7   27.61  4925.3   26.74    4952    27.5
 4966.69    26.7  4966.8   26.69 4966.91   26.69  4967.4   26.66  4978.8   21.12
  4978.9   21.07 4979.01   21.02  4979.1   20.97  4987.1   17.09  4990.8   15.29
  4992.9    14.1    4995   13.77  4995.8   13.58  4998.3   13.55  5003.5   13.64
  5005.1   13.79  5007.3   14.01  5007.7   14.26  5016.7    17.7 5022.99   20.11
  5023.1   20.15 5038.59   26.08  5038.7   26.12 5038.81   26.16  5039.1   26.27
  5039.7    26.5  5047.8   27.17  5109.6   27.38  5185.5   27.63  5198.3   27.61
  5234.8   27.56  5288.8   27.58  5326.3   27.68  5328.1   27.68  5504.6    27.9
BR U #Mann= 4
    4581      .1  4967.4    .015  5039.7      .1  5504.6      .2
BR U Banks=4967.4,5039.7
BR D #Sta/Elev= 45
    4581   28.25  4624.7   27.73  4643.6   27.57  4659.9   27.43  4702.3   27.38
  4714.8    27.4  4757.6   27.49  4779.7   27.36  4925.3   26.49    4952   27.25
 4966.69   26.45  4966.8   26.44 4966.91   26.44  4967.4   26.41  4978.8   20.87
  4978.9   20.82 4979.01   20.77  4979.1   20.72  4987.1   16.84  4990.8   15.04
  4992.9   13.85    4995   13.52  4995.8   13.33  4998.3    13.3  5003.5   13.39
  5005.1   13.54  5007.3   13.76  5007.7   14.01  5016.7   17.45 5022.99   19.86
  5023.1    19.9 5038.59   25.83  5038.7   25.87 5038.81   25.91  5039.1   26.02
  5039.7   26.25  5047.8   26.92  5109.6   27.13  5185.5   27.38  5198.3   27.36
  5234.8   27.31  5288.8   27.33  5326.3   27.43  5328.1   27.43  5504.6   27.65
BR D #Mann= 4
    4581      .1  4967.4    .015  5039.7      .1  5504.6      .2
BR D Banks=4967.4,5039.7
BC Design=,, 0 ,, 0 ,,,,,,
BC HTab HWMax=28.5
BC Use User HTab Curves=0
BC User HTab FreeFlow(D)= 0

Type RM Length L Ch R = 1 ,1137.3  ,88.3,88.3,88.3
BEGIN DESCRIPTION:
Downstream Section of Bridge/Culvert/Weir
END DESCRIPTION:
XS GIS Cut Line= 6
        3161381.     13811239.42      3161515.44     13811098.89
        3161714.     13810988.58      3161908.22     13810911.28
      3162100.04      13810783.4      3162149.88     13810745.86
#Sta/Elev= 20
    4581    28.5  4624.7   27.98  4659.9   27.68  4702.3   27.63  4757.6   27.74
  4925.3   26.74    4952    27.5  4967.4   26.66  4990.8   15.29  4992.9    14.1
  4995.8   13.58  4998.3   13.55  5003.5   13.64  5007.3   14.01  5007.7   14.26
  5039.7    26.5  5047.8   27.17  5185.5   27.63  5288.8   27.58  5504.6    27.9
#Mann= 4 , 1 , 0
    4581      .1       0  4967.4    .015       0  5039.7      .1       0
  5504.6      .2       0
#XS Ineff= 2 , 0
       0    4967    26.6  5033.1       0    26.6
Permanent Ineff=
       F       F
Bank Sta=4967.4,5039.7
XS Rating Curve= 0 ,0
Exp/Cntr=0.5,0.3

Type RM Length L Ch R = 1 ,1049.0  ,0,0,0
BEGIN DESCRIPTION:
Cross Section 1049.0
END DESCRIPTION:
XS GIS Cut Line= 3
      3161485.77     13811200.82      3161761.12      13811059.9
      3161859.15     13811010.05
#Sta/Elev= 18
  4691.2    27.9  4791.2    26.9  4911.2    27.9  4931.2    27.3  4941.2    26.6
  4951.2    25.3  4966.6   25.62  4967.6   25.84  4968.6   24.66  4994.5   12.95
  4994.9   12.87  4999.3   12.68  5005.2   12.94  5005.4   13.02  5031.7   24.82
  5045.4   26.06    5059   26.24  5110.5    28.1
#Mann= 3 , 1 , 0
  4691.2      .1       0  4968.6    .015       0  5031.7      .1       0
Bank Sta=4968.6,5031.7
XS Rating Curve= 0 ,0
Exp/Cntr=0.3,0.1

Chan Stop Cuts=-1
Use User Specified Reach Order=0
Composite Channel Slope=5